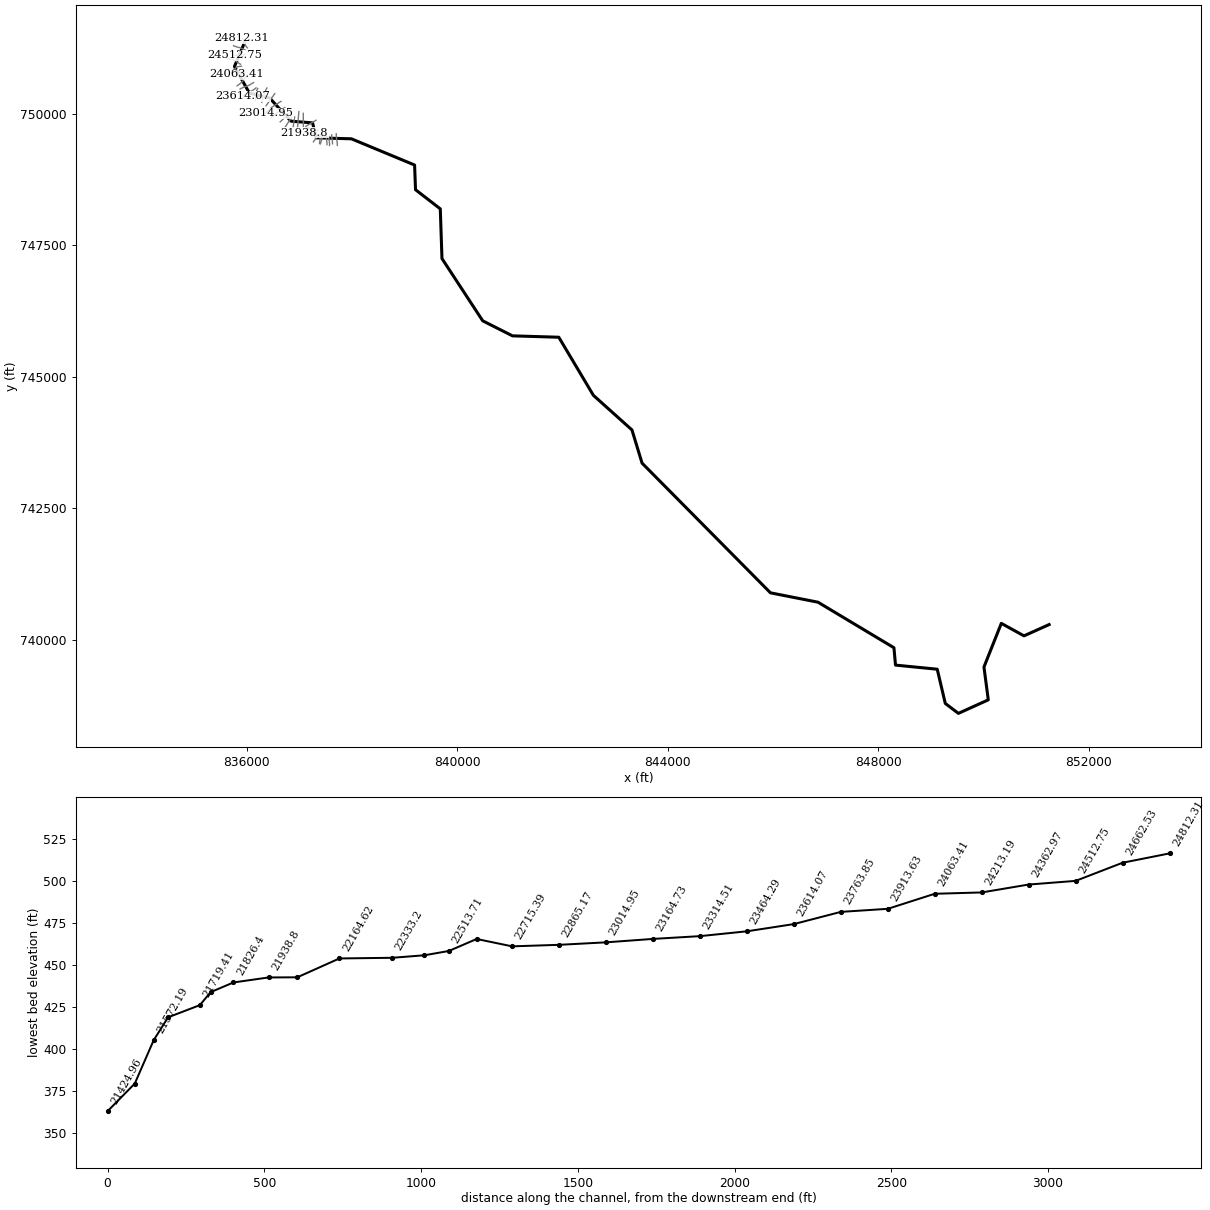
--- 8524_ras.prj (project) ---

Proj Title=8524
Current Plan=p01
Default Exp/Contr=0.3,0.1
English Units
Geom File=g01
Flow File=f01
Plan File=p01
Y Axis Title=Elevation
X Axis Title(PF)=Main Channel Distance
X Axis Title(XS)=Station
BEGIN DESCRIPTION:
RFD model 8524 exported to HEC-RAS
END DESCRIPTION:

--- 8524_ras.p01 (plan) ---

Plan Title=Plan 01
Program Version=4.10
Short Identifier=Plan 01
Geom File=g01
Flow File=f01
Subcritical Flow
Calc Critical at every XS
Secant Critical Depth

--- 8524_ras.f01 (steady flow) ---

Flow Title=Flow 01
Program Version=5.01
Number of Profiles= 6
Profile Names=10yr,25yr,50yr,100yr,100plus,500yr
River Rch & RM=8524,81,24812.31
  693.61 1046.77 1361.81 1624.53 2371.82 3168.37
River Rch & RM=8524,81,24662.53
  695.49 1049.67 1365.65 1629.18  2378.6  3176.4
River Rch & RM=8524,81,24512.75
  697.75 1053.15 1370.26 1634.74 2386.73 3186.02
River Rch & RM=8524,81,24362.97
  707.87  1068.8 1390.95 1659.75 2423.24 3229.19
River Rch & RM=8524,81,24213.19
  708.99 1070.54 1393.24 1662.53 2427.29 3233.97
River Rch & RM=8524,81,24063.41
  710.49 1072.85  1396.3 1666.22 2432.68 3240.35
River Rch & RM=8524,81,23913.63
  711.99 1075.16 1399.36 1669.92 2438.08 3246.71
River Rch & RM=8524,81,23763.85
  712.73 1076.32 1400.89 1671.77 2440.78  3249.9
River Rch & RM=8524,81,23614.07
 1174.24 1777.29 2317.71 2768.57 4042.11 5019.99
River Rch & RM=8524,81,23464.29
 1177.55 1782.45 2324.56 2776.87 4054.23 5033.39
River Rch & RM=8524,81,23314.51
 1179.22 1785.03 2327.98 2781.02 4060.29 5040.09
River Rch & RM=8524,81,23164.73
 1182.19 1789.66 2334.14 2788.48 4071.19 5052.13
River Rch & RM=8524,81,23014.95
  1188.1 1798.87 2346.38 2803.35 4092.89 5076.18
River Rch & RM=8524,81,22865.17
 1192.36 1805.51 2355.22 2814.08 4108.55 5093.53
River Rch & RM=8524,81,22715.39
 1193.02 1806.54 2356.58 2815.73 4110.96 5096.19
River Rch & RM=8524,81,22602.37
 1289.27 1955.26 2553.29 3053.37 4457.93 5473.36
River Rch & RM=8524,81,22513.71
 1290.89 1957.78 2556.64 3057.43 4463.85 5479.84
River Rch & RM=8524,81, 22333.2
 1292.82 1960.79 2560.65  3062.3 4470.96 5487.61
River Rch & RM=8524,81,22164.62
 1293.79  1962.3 2562.66 3064.74 4474.52 5491.49
River Rch & RM=8524,81,22030.23
 1296.69 1966.83 2568.67 3072.04 4485.17 5503.14
River Rch & RM=8524,81, 21938.8
 1298.31 1969.34 2572.01 3076.09 4491.09  5509.6
River Rch & RM=8524,81, 21826.4
 1300.24 1972.35 2576.02 3080.96 4498.19 5517.36
River Rch & RM=8524,81,21753.79
 1301.85 1974.86 2579.36 3085.01 4504.11 5523.82
River Rch & RM=8524,81,21618.05
 1436.99 2183.21 2854.59 3417.08 4988.94 6041.39
River Rch & RM=8524,81,21511.91
 1438.26 2185.18 2857.21 3420.25 4993.57 6046.38
River Rch & RM=8524,81,21424.96
 1439.83 2187.64 2860.48 3424.22 4999.36 6052.61
River Rch & RM=8524,81,21277.74
 1440.78 2189.11 2862.44  3426.6 5002.84 6056.34
River Rch & RM=8524,81,21088.13
 2381.39 3634.87 4769.22 5722.64 8355.06 9451.83
River Rch & RM=8524,81,20785.58
 2387.49 3644.44 4782.02 5738.25 8377.84 9474.83
River Rch & RM=8524,81,20638.35
 2391.31 3650.46  4790.1 5748.11 8392.25 9489.46
River Rch & RM=8524,81,20491.13
 2397.38 3660.01 4802.87 5763.69 8414.99 9512.42
River Rch & RM=8524,81, 20343.9
 2399.59 3663.49 4807.52 5769.35 8423.26 9520.76
River Rch & RM=8524,81,20196.68
 2404.82 3671.71 4818.53 5782.78 8442.86 9540.57
River Rch & RM=8524,81,20049.45
    2407 3675.15 4823.14 5788.42 8451.09  9548.9
River Rch & RM=8524,81,19902.22
 2411.94 3682.92 4833.54 5801.11 8469.62 9567.64
River Rch & RM=8524,81,19607.77
 2417.67 3691.95 4845.65  5815.9 8491.21 9589.49
River Rch & RM=8524,81,19460.55
 2418.72 3693.63 4847.91 5818.67 8495.26 9593.65
River Rch & RM=8524,81,19374.65
 2423.71 3701.57 4858.63 5831.84 8514.49  9613.4
River Rch & RM=8524,81,19252.64
 2427.37 3707.41 4866.52 5841.54 8528.64 9627.94
River Rch & RM=8524,81,19008.06
 2428.68  3709.5 4869.33    5845  8533.7 9633.13
River Rch & RM=8524,81,18865.55
 2433.62 3717.39    4880 5858.12 8552.85 9652.84
River Rch & RM=8524,81,18724.42
 2438.72 3725.59 4891.11 5871.83 8572.87 9673.58
River Rch & RM=8524,81,18577.19
    2440 3727.64 4893.89 5875.26 8577.87 9678.76
River Rch & RM=8524,81,18429.97
  2445.7 3736.75 4906.21 5890.41 8600.01 9701.55
River Rch & RM=8524,81,18107.53
 2448.01 3740.45 4911.22 5896.59 8609.02 9710.86
River Rch & RM=8524,81,17857.91
 2650.74 4060.67 5341.03 6422.14 9376.3310483.35
River Rch & RM=8524,81,17608.29
 2661.09 4077.36 5363.72 6450.21 9417.3110525.49
River Rch & RM=8524,81,17358.68
 2663.05 4080.52 5368.03 6455.55  9425.110533.51
River Rch & RM=8524,81,17109.06
 2903.78  4464.9 5887.51 7094.5710358.0811473.48
River Rch & RM=8524,81,16859.44
 2908.59 4472.67 5898.07 7107.6510377.1711492.86
River Rch & RM=8524,81,16609.82
 3539.93 5409.99 7106.64 8531.1312455.4513324.91
River Rch & RM=8524,81, 16360.2
 5716.57 8788.0511593.4313961.2420383.4120473.39
River Rch & RM=8524,81,16110.59
 5718.23 8790.7411597.1113965.8120390.0820479.56
River Rch & RM=8524,81,15860.97
 5741.78 8828.91 11649.214030.3620484.3220566.72
River Rch & RM=8524,81,15611.35
 5745.73 8835.3211657.95 14041.220500.1520581.36
River Rch & RM=8524,81,15361.73
 5746.77    883711660.2414044.0520504.3120585.21
River Rch & RM=8524,81,15112.11
 6179.42 9529.8212598.9815200.1722192.2522113.23
River Rch & RM=8524,81, 14862.5
 6308.82 9738.7512883.5515552.2222706.2422580.18
River Rch & RM=8524,81,14612.88
 6309.43 9739.74 12884.915553.8922708.68 22582.4
River Rch & RM=8524,81,14363.26
 6315.94  9750.312899.3115571.7622734.7722606.17
River Rch & RM=8524,81,14113.64
 6383.72  9860.213049.3815757.8423006.4522853.65
River Rch & RM=8524,81,13864.02
 6388.59 9868.0913060.1715771.2123025.9622871.39
River Rch & RM=8524,81,13614.41
 6390.21 9870.7313063.7615775.6623032.4722877.31
River Rch & RM=8524,81,13364.79
 6422.27 9922.6813134.6715863.56 23160.822993.96
River Rch & RM=8524,81,13115.17
 6447.56 9963.6713190.6615932.9823262.1623086.09
River Rch & RM=8524,81,12211.42
 6464.94 9991.8713229.1515980.7223331.8523149.39
River Rch & RM=8524,81,11359.22
 6546.5110123.9913409.4816204.2123658.1423445.12
River Rch & RM=8524,81,9894.421
 6633.4610264.9413601.9416442.8324006.5323760.51
River Rch & RM=8524,81,8919.208
 6804.1310541.1113978.6616909.52 24687.924374.16
River Rch & RM=8524,81,7626.958
 6839.1710597.76 14055.917005.1624827.5324499.47
River Rch & RM=8524,81,6723.197
 6868.1110644.5714119.73 17084.224942.9324602.98
River Rch & RM=8524,81,5746.556
 6906.8210707.1814205.1217189.9725097.3624741.46
River Rch & RM=8524,81, 4504.28
 6909.2210711.0614210.4217196.5325106.9424750.06
Boundary for River Rch & Prof#=8524,81,1
Up Type= 0
Dn Type= 2
Boundary for River Rch & Prof#=8524,81,2
Up Type= 0
Dn Type= 2
Boundary for River Rch & Prof#=8524,81,2
Up Type= 0
Dn Type= 2
Boundary for River Rch & Prof#=8524,81,2
Up Type= 0
Dn Type= 2
Boundary for River Rch & Prof#=8524,81,2
Up Type= 0
Dn Type= 2
Boundary for River Rch & Prof#=8524,81,2
Up Type= 0
Dn Type= 2

--- 8524_ras.g01 (geometry) ---

Geom Title=8524
Program Version=4.10

River Reach=8524,81
Reach XY= 30
835953.609353641751349.845128443835764.036858157 750898.89443217
836047.444495929750395.964495996836434.609774826750298.851029367
836836.530159964749860.547777969837248.556774459749828.332558211
837316.889800663749543.968358344837986.363389273749525.383723139
839187.119801486749026.877855327839205.143430813748557.808122863
 839675.71220537748193.816307196839707.486930979 747249.56013953
840481.926849095746066.262683849841047.654868178745780.673285581
841927.619464335745754.530950826842584.594946461744651.062952574
843317.994955553743992.892373312843510.112335386743361.773617783
845950.221748044740897.223547356846853.535154224740719.006024774
848296.588941492739853.972557162848326.391458831739523.663674052
 849119.36020888739445.538674043 849272.44469301738795.169813081
849521.605373692738606.449141946850089.412292188738863.507424042
850007.381042203739487.205340704850337.113651251 740316.92095501
850767.797708882740079.653257464 851246.00941417740294.120707969

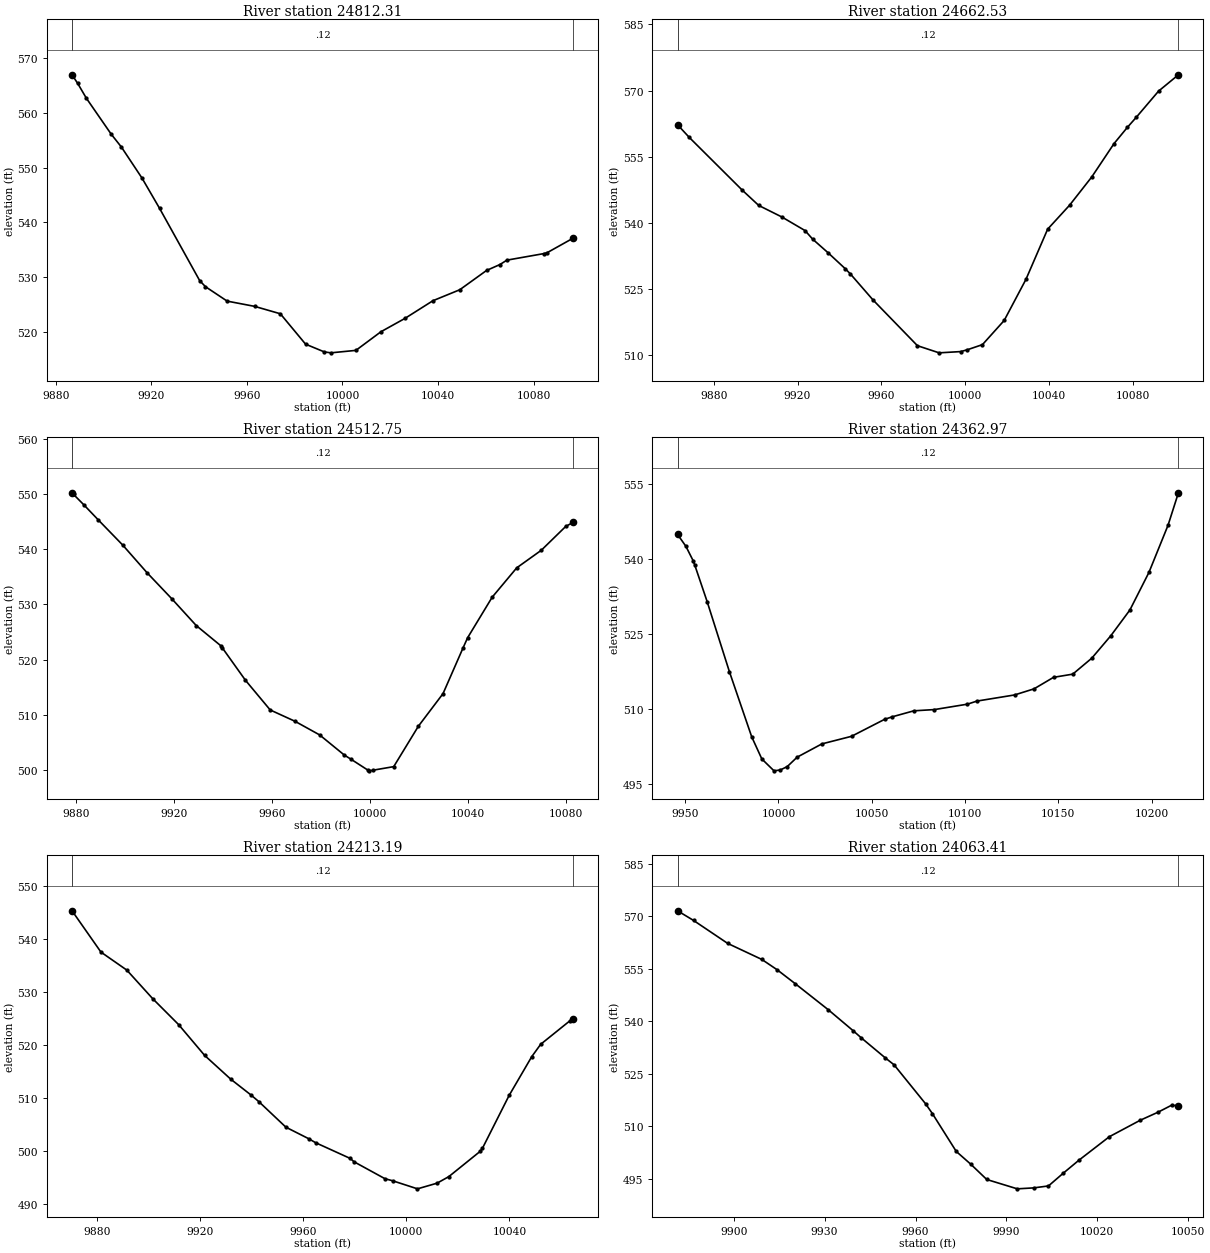
Type RM Length L Ch R = 1 ,24812.31,149.779700,149.779700,149.779700
XS GIS Cut Line= 6
836009.232220305751253.326722436 835982.60024316751283.745425665
835963.692905773 751316.98338603 835944.73153593751374.524164811
835926.709116052751410.026466576835908.656028384751434.647114293
#Sta/Elev= 26
9886.829 567.0049889.182565.4382 9892.85562.70449903.242556.13349907.507553.7808
9916.095548.12649923.478542.57329940.259529.36199942.682 528.2519951.764525.6099
9963.268524.65119974.022523.2962 9984.59517.73889992.432516.32289995.158516.1525
10005.64516.601910016.14520.012210026.14522.439510037.89525.684210049.11527.6867
10060.32531.214110065.96 532.30610068.85533.104610084.53534.316310085.76534.4832
10096.49537.1044
#Mann= 3 , 0 , 0
9886.829    0.12       09886.829    0.12       010096.49    0.12       0
#XS Ineff= 2 , 0
       0                               0
Bank Sta=9886.829,10096.49
Exp/Cntr=0.3,0.1

Type RM Length L Ch R = 1 ,24662.53,149.779700,149.779700,149.779700
XS GIS Cut Line= 6
835970.061356676751211.866563359835911.673625983751239.222536135
835873.321864754751254.620481917835841.927311272751262.705394227
835797.716461281751274.738466385835746.099709481751293.177153331
#Sta/Elev= 26
9862.771562.28439868.361 559.4189893.727547.4218 9901.49543.99819912.533541.3798
9923.577538.3002 9927.25536.34289934.441533.32559942.756 529.6589945.217528.4665
9955.993522.58179977.179512.21449987.516510.59629997.853510.8821   10001511.2985
10008.18512.457910018.54517.929710028.91527.234210039.27538.6201 10049.7544.0318
10060.32550.464210070.94558.021410077.32561.707610081.56563.985510092.18569.9107
10101.63573.6038
#Mann= 3 , 0 , 0
9862.771    0.12       09862.771    0.12       010101.63    0.12       0
#XS Ineff= 2 , 0
       0                               0
Bank Sta=9862.771,10101.63
Exp/Cntr=0.3,0.1

Type RM Length L Ch R = 1 ,24512.75,149.779700,149.779700,149.779700
XS GIS Cut Line= 6
835965.628877281751122.342896375835960.686140484751122.795027305
835904.444365497751121.537848231835843.595521331751113.907941907
835806.971420835751110.094500815835762.077082242751110.682714678
#Sta/Elev= 29
9878.455 550.2819879.087 549.9789883.419548.03019889.106545.38239899.109540.7989
9909.111535.73689919.114531.05369929.116526.17599939.119522.51449939.675522.1721
9949.192516.2354 9959.27510.85469969.348508.80569979.426506.32469989.504502.6637
9992.375501.8663    9999499.96269999.583499.8025   10001499.903610009.64500.5662
 10019.7507.907210029.75 513.82310037.82522.028110039.79523.978510049.79531.3262
 10059.8536.6553 10069.8 539.838 10079.8544.178910082.72544.8886
#Mann= 3 , 0 , 0
9878.455    0.12       09878.455    0.12       010082.72    0.12       0
#XS Ineff= 2 , 0
       0                               0
Bank Sta=9878.455,10082.72
Exp/Cntr=0.3,0.1

Type RM Length L Ch R = 1 ,24362.97,149.779700,149.779700,149.779700
XS GIS Cut Line= 6
835879.215622647750942.111133291835828.989031835750972.360612479
835779.247293661751011.098809727 835744.26378514751027.109910202
835702.229474058751040.076534232835639.482128525751052.835811085
#Sta/Elev= 30
9945.913544.91959950.408542.53639954.238539.69679955.104538.8472 9961.79531.4784
9973.738517.44739985.685504.42729991.104500.00499997.633497.6251   10001497.8013
10004.74498.477210010.03500.3582 10023.3503.014910039.18504.530910056.89507.9229
10061.01508.433110072.59509.630510083.59509.878410101.32510.960810106.39511.5777
10126.55512.802610137.02514.025810147.48516.330310157.77516.965210167.98520.1616
10178.19 524.65310188.41529.800710198.62537.318310208.84546.735610214.42553.2452
#Mann= 3 , 0 , 0
9945.913    0.12       09945.913    0.12       010214.42    0.12       0
#XS Ineff= 2 , 0
       0                               0
Bank Sta=9945.913,10214.42
Exp/Cntr=0.3,0.1

Type RM Length L Ch R = 1 ,24213.19,149.779600,149.779600,149.779600
XS GIS Cut Line= 6
835896.185699618750903.607636269835827.244000654750896.285121256
835807.011076774750886.719417581835777.755364299750861.257989035
835745.825549484750839.075955201835723.921983532750827.577754376
#Sta/Elev= 26
9870.429545.27969881.645537.49919891.672534.10859901.699528.73319911.726523.8607
9921.842518.04649931.963513.57099939.813510.5922 9942.82509.36059953.357504.5265
9962.193502.36119964.893501.60389978.317498.6408 9979.76498.01899991.741494.8351
9994.749494.438910004.36492.924410011.97 493.99510016.53495.235210028.71 500.003
 10029.5500.520710039.88510.509610048.65517.810310052.11520.1371 10063.4524.5449
10064.62524.8178
#Mann= 3 , 0 , 0
9870.429    0.12       09870.429    0.12       010064.62    0.12       0
#XS Ineff= 2 , 0
       0                               0
Bank Sta=9870.429,10064.62
Exp/Cntr=0.3,0.1

Type RM Length L Ch R = 1 ,24063.41,149.779700,149.779700,149.779700
XS GIS Cut Line= 6
835959.698649317750790.162769737835930.568207101750775.035161742
835882.826407469750756.541325064835870.237301906750755.032311284
  835825.8899228750759.835094687835802.869900793 750754.39920846
#Sta/Elev= 26
9881.447571.54329886.741568.78279898.009562.22329909.277557.64629914.359 554.681
9920.343550.69339931.247543.25139939.436537.27649942.152 535.2159950.062529.5048
9952.916527.55859963.308516.44389965.567513.6265 9973.45502.81479978.247499.1585
9983.522494.79949993.595492.1314    9999492.402910003.89492.961710008.74 496.578
10013.96500.325810023.98507.019110034.16511.713610040.03514.011710044.52516.0086
10046.78515.8392
#Mann= 3 , 0 , 0
9881.447    0.12       09881.447    0.12       010046.78    0.12       0
#XS Ineff= 2 , 0
       0                               0
Bank Sta=9881.447,10046.78
Exp/Cntr=0.3,0.1

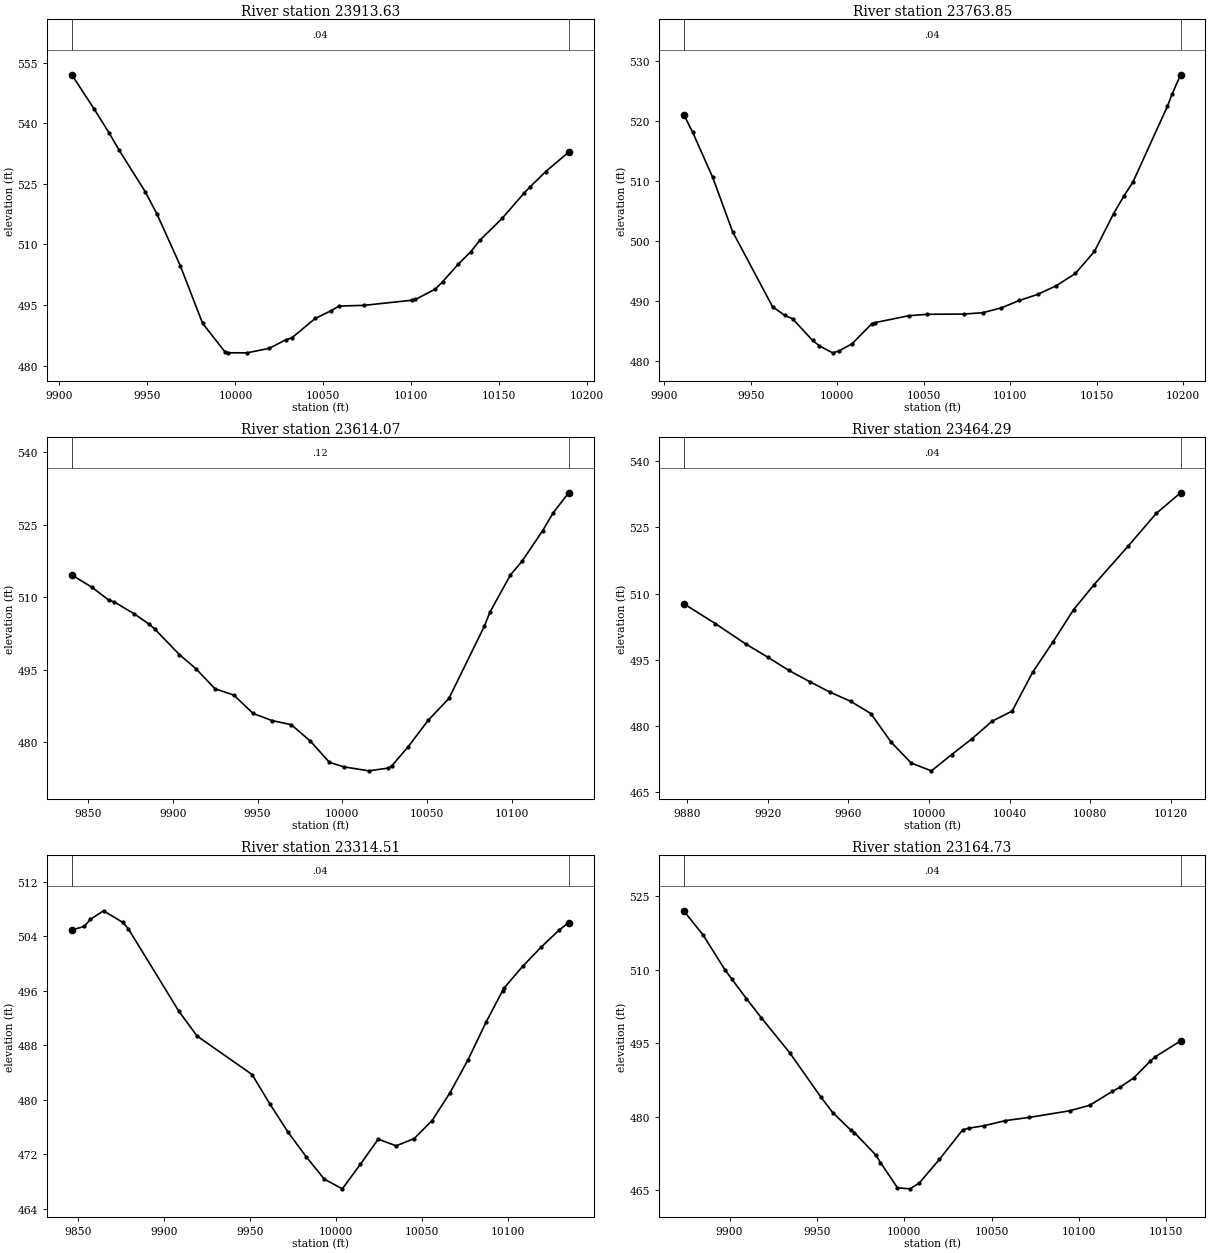
Type RM Length L Ch R = 1 ,23913.63,149.779700,149.779700,149.779700
XS GIS Cut Line= 6
836014.483522538 750729.39725707835973.706654646750687.421999834
835918.070885188750618.069453796835891.102609037750591.313312974
 835863.15565629750567.718935741835814.429352877750532.173209645
#Sta/Elev= 30
9907.026551.99669919.827543.44979928.364 537.5049933.928533.32289948.807523.0217
9955.375517.58479968.683504.74349981.371490.4736 9994.06483.4385    9996483.1946
10006.62483.179510019.23484.2888 10028.5486.367910032.27486.949810045.43491.7164
10054.55493.631710058.91494.753410073.11494.932610100.53496.206710102.33496.3906
10113.61 498.96310117.83500.7947 10126.7 505.13710133.73508.186710139.21511.1537
10151.59516.439810163.96522.651110167.66524.319710176.34528.024410189.43532.8532
#Mann= 3 , 0 , 0
9907.026    0.04       09907.026    0.04       010189.43    0.04       0
#XS Ineff= 2 , 0
       0                               0
Bank Sta=9907.026,10189.43
Exp/Cntr=0.3,0.1

Type RM Length L Ch R = 1 ,23763.85,149.779700,149.779700,149.779700
XS GIS Cut Line= 6
836129.429946882750594.287149536836053.572093807750550.323019544
836033.525443099750539.477669613835936.635677827750504.078100981
 835899.39811334750486.792998395835870.676677932  750471.4129228
#Sta/Elev= 30
9911.323521.10299916.443518.19059928.001510.68249939.559501.58489962.675489.0518
 9969.73487.60529974.233487.03859985.792483.44399989.673482.5404 9997.35481.3572
   10001481.655510008.75482.891510020.12486.229210021.79486.391110041.52487.5548
10052.16487.786510073.46487.8326 10084.1488.047510094.75488.843610105.39490.0905
10116.04491.120910126.75492.559210137.77494.5979 10148.8498.285610159.82504.5662
   10166507.603310170.99509.815110190.98522.499210193.68524.522810198.58527.7493
#Mann= 3 , 0 , 0
9911.323    0.04       09911.323    0.04       010198.58    0.04       0
#XS Ineff= 2 , 0
       0                               0
Bank Sta=9911.323,10198.58
Exp/Cntr=0.3,0.1

Type RM Length L Ch R = 1 ,23614.07,149.779700,149.779700,149.779700
XS GIS Cut Line= 6
836173.548980973750493.105877742836157.418290949750478.294906849
836116.300041304750450.365003882836043.549883512 750412.81111051
836004.193318984750389.778254547835927.794757605750335.486839761
#Sta/Elev= 30
9840.546514.60499852.531512.03699862.445509.36619865.368509.06079877.457506.5471
9886.106504.43339889.546503.37979903.903498.15549913.615495.25179924.869491.0894
9936.122489.74579947.376485.9644 9958.63 484.4869969.884483.63849981.137480.2522
9992.391475.8518   10001 474.91110015.58474.094410027.14474.669910029.22475.1577
10038.69479.028810050.74484.602510062.83489.073710083.71504.012310087.02506.9417
10099.11 514.62510105.85517.417110118.04523.758310124.22527.4276 10133.4531.6106
#Mann= 3 , 0 , 0
9840.546    0.12       09840.546    0.12       0 10133.4    0.12       0
#XS Ineff= 2 , 0
       0                               0
Bank Sta=9840.546,10133.4
Exp/Cntr=0.3,0.1

Type RM Length L Ch R = 1 ,23464.29,149.779700,149.779700,149.779700
XS GIS Cut Line= 6
836206.666118767750482.237592547836188.018810723750444.907482183
836182.315907494750426.123839888836178.824160107750407.649810812
836173.495294419750321.536399696836156.117550639 750243.41182939
#Sta/Elev= 23
9878.282507.70839893.944503.20869908.998498.59029920.067495.56119930.421 492.589
9940.841490.01939951.018487.62229961.153485.57639971.174482.78499981.195476.3328
9991.216471.561110001.23469.802610011.25473.486810021.27477.045110031.29481.0334
10041.31483.366610051.43492.1285 10061.6499.062610071.78506.352810081.96512.0365
10098.89520.780910112.82528.1866 10124.9532.8704
#Mann= 3 , 0 , 0
9878.282    0.04       09878.282    0.04       0 10124.9    0.04       0
#XS Ineff= 2 , 0
       0                               0
Bank Sta=9878.282,10124.9
Exp/Cntr=0.3,0.1

Type RM Length L Ch R = 1 ,23314.51,149.779700,149.779700,149.779700
XS GIS Cut Line= 6
836379.906382133750491.445720535836363.007160631750458.287735955
836340.828721291750400.747416222836323.762417366750347.474907568
836300.723351288750271.938295168836281.945447554750219.855217041
#Sta/Elev= 28
9846.178504.94659853.412505.48189856.983506.51379864.636507.7762 9875.86506.0589
9879.005 505.1529908.352493.06549919.069489.37389951.095483.71589961.596479.3298
9972.096475.22229982.596 471.6349993.096468.352810003.59466.922910014.04470.5015
 10024.5474.225910034.95473.241210045.41474.304210055.86476.955910066.32481.0563
10076.77485.887110087.35491.449510096.85496.017410097.98496.492410108.61499.6256
10119.24502.416610129.87504.963210135.34506.0224
#Mann= 3 , 0 , 0
9846.178    0.04       09846.178    0.04       010135.34    0.04       0
#XS Ineff= 2 , 0
       0                               0
Bank Sta=9846.178,10135.34
Exp/Cntr=0.3,0.1

Type RM Length L Ch R = 1 ,23164.73,149.779600,149.779600,149.779600
XS GIS Cut Line= 5
836531.111039901750384.070263273836457.589202099750282.673551759
836456.380429139 750281.08016922836436.462204483750254.154955629
836365.037511051750153.139972468
#Sta/Elev= 30
9873.753522.04519884.957517.03919897.309510.02789901.199508.14199909.661504.0974
9918.234500.17499934.366493.08999952.305483.9994 9959.07480.8455 9969.34 477.285
9971.422 476.7729983.774472.15999986.375470.64939996.126465.482210003.32465.2768
10008.56466.445310020.14471.291510033.44477.315710037.02477.6633 10045.7478.1535
10057.95479.210610071.67479.866310094.69481.207810106.31 482.35810119.19485.1882
10123.63486.039810131.43487.931710140.95 491.38710143.68492.240510158.21495.4571
#Mann= 3 , 0 , 0
9873.753    0.04       09873.753    0.04       010158.21    0.04       0
#XS Ineff= 2 , 0
       0                               0
Bank Sta=9873.753,10158.21
Exp/Cntr=0.3,0.1

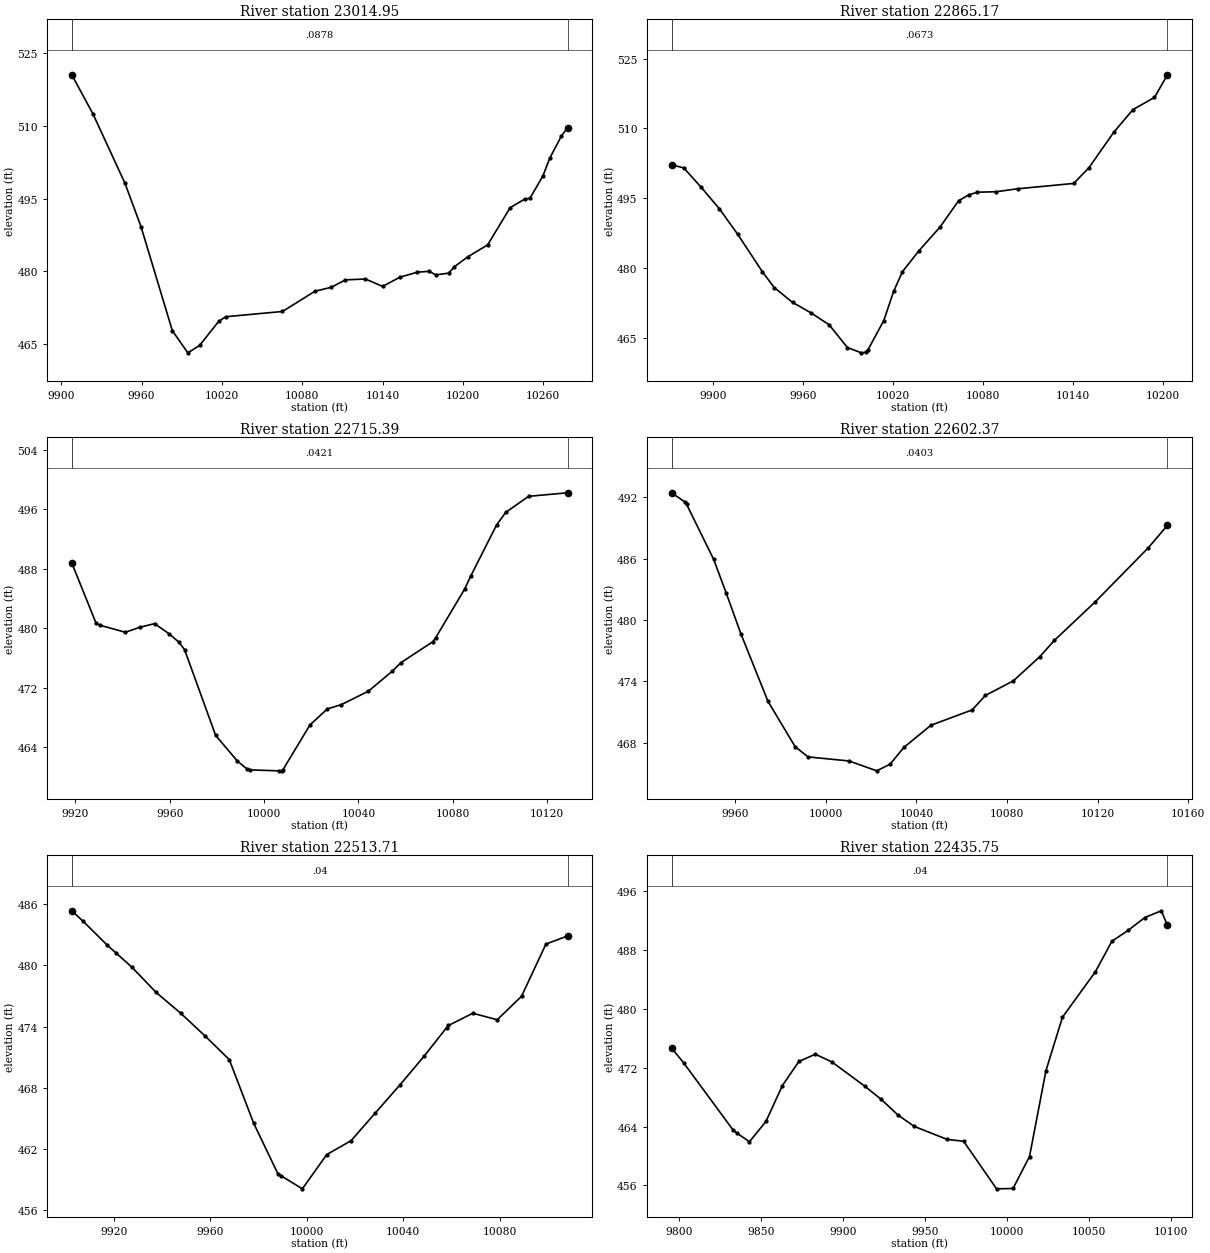
Type RM Length L Ch R = 1 ,23014.95,149.779700,149.779700,149.779700
XS GIS Cut Line= 6
836647.721733251750236.460079899836534.582085166750165.548508514
836481.879325186750129.288062533 836436.70382362750092.694959256
836389.984116246750048.533366381836355.977401262  750011.4981613
#Sta/Elev= 30
9907.902520.52919923.723512.47769947.668498.1555 9959.64489.21579982.994467.8226
 9994.57463.236610003.38464.763510017.78469.767810022.99470.678210065.29471.7592
10089.57475.9331 10101.7476.7411 10112.3478.268610127.21478.451910140.08 476.923
10152.95478.816410165.97479.852510174.83480.038810179.73479.301810189.39479.6538
10193.49480.941910203.95 483.064 10218.5485.482410235.29 493.13410246.29494.9321
10250.07495.061110259.87499.734510264.86503.321610273.44507.8239 10278.2 509.664
#Mann= 3 , 0 , 0
9907.902  0.0878       09907.902  0.0878       0 10278.2  0.0878       0
#XS Ineff= 2 , 0
       0                               0
Bank Sta=9907.902,10278.2
Exp/Cntr=0.3,0.1

Type RM Length L Ch R = 1 ,22865.17,149.779800,149.779800,149.779800
XS GIS Cut Line= 6
836721.163431476 750119.61777263836617.376848113750047.321559688
 836604.00488869750038.217084517836547.401258179749995.915645047
836497.223331028749955.004572507836458.640160778749919.438999967
#Sta/Elev= 30
9872.515502.16699880.594501.50949892.214497.34369904.401492.69879916.588487.2355
 9933.08479.15179940.962475.77739953.149472.59599965.336470.36699977.523467.7912
 9989.71462.8935    9999461.757210001.85461.898310003.17462.268310013.97468.7025
10020.55474.997710026.42 479.20510037.26483.650510051.39488.765510063.87494.4614
10070.67495.714610076.36496.285710088.94496.388310103.12497.018310140.55 498.169
10150.59501.486110167.21509.1365 10180.1514.048510194.41516.643410203.06 521.524
#Mann= 3 , 0 , 0
9872.515  0.0673       09872.515  0.0673       010203.06  0.0673       0
#XS Ineff= 2 , 0
       0                               0
Bank Sta=9872.515,10203.06
Exp/Cntr=0.3,0.1

Type RM Length L Ch R = 1 ,22715.39,113.025700,113.025700,113.025700
XS GIS Cut Line= 6
836783.282738024749992.078198797836727.833344381749949.120722778
 836715.98829458749936.214609905836701.856412855749913.648475417
836687.739338943749897.383777999836632.763929526749847.314200268
#Sta/Elev= 30
9918.496488.80419928.778480.71279930.441480.42799941.192479.47979947.317480.1469
9953.607480.63929959.797479.26229963.866478.16139966.323477.14749979.486465.6239
 9988.67462.1796 9992.86461.07629994.263460.978110006.19460.850810007.63 460.872
10008.02460.984710019.49467.025310026.88469.177810032.82469.753610044.27471.5588
10054.35474.231810058.06475.389810071.59478.210110072.75 478.72310085.11485.3036
 10087.6486.994610098.64493.919410102.45495.582810112.16497.751710128.71498.2306
#Mann= 3 , 0 , 0
9918.496  0.0421       09918.496  0.0421       010128.71  0.0421       0
#XS Ineff= 2 , 0
       0                               0
Bank Sta=9918.496,10128.71
Exp/Cntr=0.3,0.1

Type RM Length L Ch R = 1 ,22602.37,88.655800,88.655800,88.655800
XS GIS Cut Line= 2
836848.251178253749930.470580528836727.433885168749747.995071726
#Sta/Elev= 22
9931.972492.43819937.862491.53429938.533491.32549950.527485.92419955.976  482.68
 9962.52478.65469974.513472.02839986.506467.59619992.203466.599910010.32466.2016
10022.49465.237210028.43465.891110034.48467.529110046.47469.700910064.66471.2016
10070.46  472.6110082.77474.034910094.45476.397810100.89477.9922   10119 481.778
10142.42 487.06810150.82 489.251
#Mann= 3 , 0 , 0
9931.972  0.0403       09931.972  0.0403       010150.82  0.0403       0
#XS Ineff= 2 , 0
       0                               0
Bank Sta=9931.972,10150.82
Exp/Cntr=0.3,0.1

Type RM Length L Ch R = 1 ,22513.71,77.963300,77.963300,77.963300
XS GIS Cut Line= 2
836907.654632976749939.663949735836877.692853984749736.115623462
#Sta/Elev= 25
9902.491 485.3369907.205484.30789917.313481.9442 9920.72 481.232 9927.42479.8181
9937.528477.33219947.636475.31589957.744 473.0849967.851470.75999977.959464.5358
9988.067459.55299989.388459.37339998.175458.098210008.28461.451310018.39462.8133
 10028.5465.545610038.61 468.26110048.71471.094910058.06473.895410058.82474.1036
10068.93475.296510079.04474.662710089.14476.960610099.25482.073410108.23482.8713
#Mann= 3 , 0 , 0
9902.491    0.04       09902.491    0.04       010108.23    0.04       0
#XS Ineff= 2 , 0
       0                               0
Bank Sta=9902.491,10108.23
Exp/Cntr=0.3,0.1

Type RM Length L Ch R = 1 ,22435.75,102.554100,102.554100,102.554100
XS GIS Cut Line= 2
836988.393553268750042.235346231 836962.69575368749741.279735223
#Sta/Elev= 27
9795.708474.6825 9802.97472.69989833.079463.56139835.596463.09819843.115461.9482
9853.152464.70439863.188469.59499873.224472.86549883.261473.85489893.297472.8101
 9913.37469.50439923.406467.71079933.443465.61269943.479464.03789963.552 462.267
9973.588462.01889993.661455.5436 10003.7 455.59210013.73459.933210023.77471.6314
10033.81478.887110053.88485.071110063.92489.221510073.95490.718610083.99492.4491
10094.02493.364410097.76 491.398
#Mann= 3 , 0 , 0
9795.708    0.04       09795.708    0.04       010097.76    0.04       0
#XS Ineff= 2 , 0
       0 9916.46                       0
Bank Sta=9795.708,10097.76
Exp/Cntr=0.3,0.1

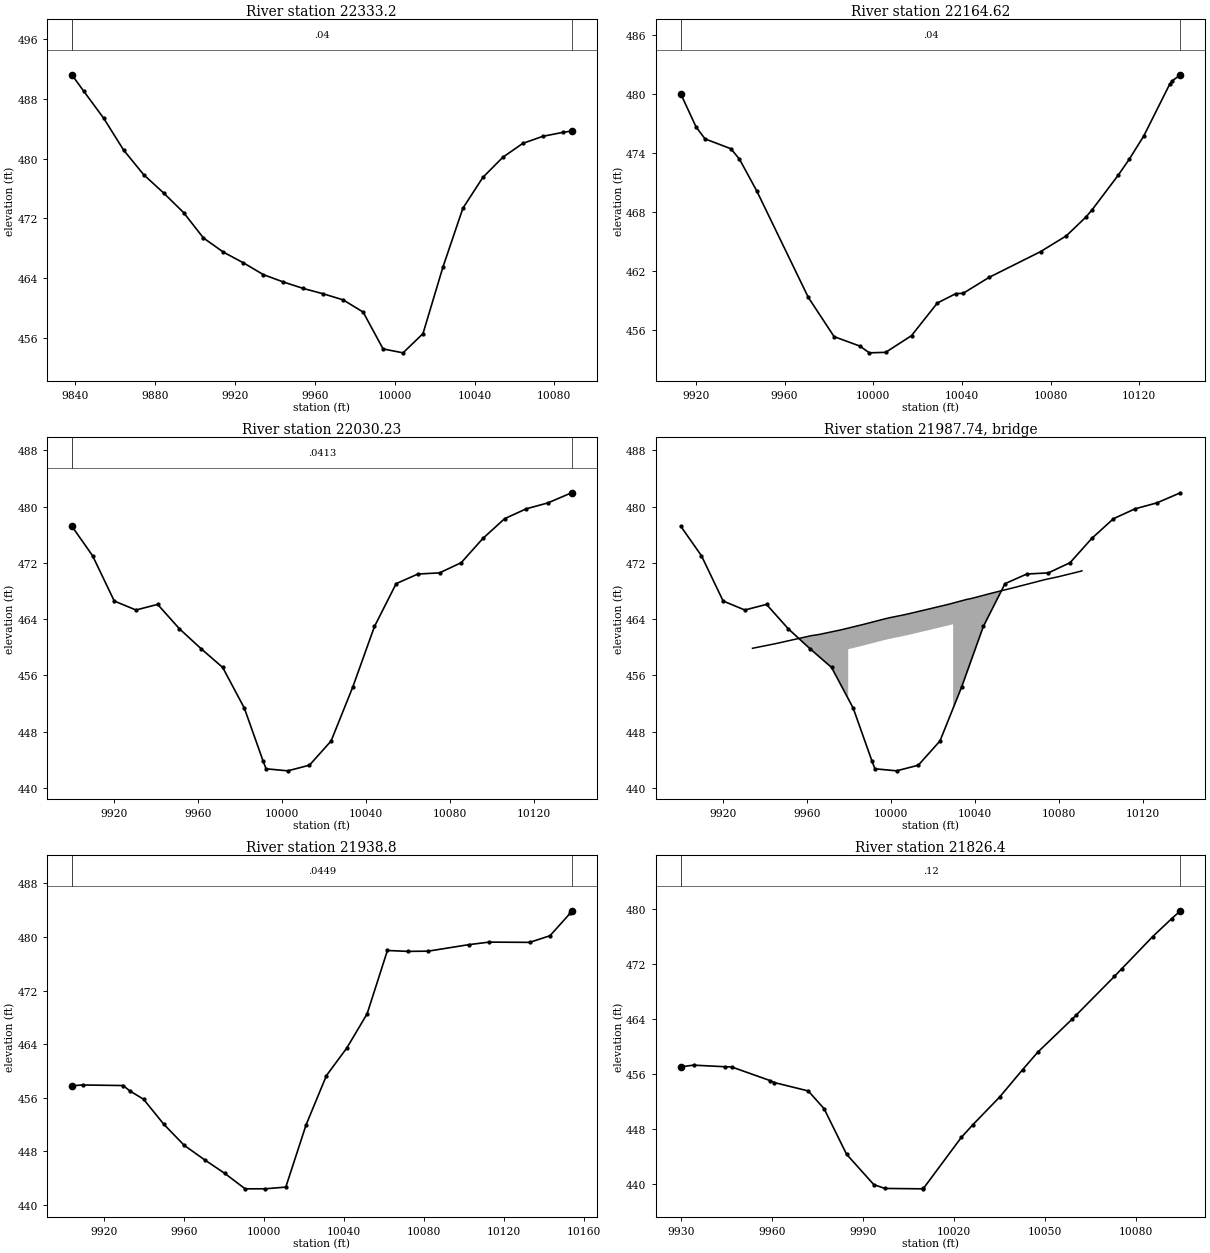
Type RM Length L Ch R = 1 , 22333.2,168.578900,168.578900,168.578900
XS GIS Cut Line= 2
837071.683772023750010.968347222837073.762175697749760.560906019
#Sta/Elev= 27
9838.219491.20859844.188489.01549854.188485.39579864.188481.13579874.189477.8638
9884.189475.41599894.189 472.798 9904.19469.3933 9914.19467.4995 9924.19466.0759
9934.191464.49819944.191463.51689954.191  462.659964.192461.93599974.192461.1212
9984.192459.49329994.193454.565410004.19454.044410014.19456.615710024.19465.5144
10034.19473.375810044.19477.494810054.19480.1837 10064.2482.0373 10074.2482.9799
 10084.2 483.50810088.64483.6855
#Mann= 3 , 0 , 0
9838.219    0.04       09838.219    0.04       010088.64    0.04       0
#XS Ineff= 2 , 0
       0 9894.65                       0
Bank Sta=9838.219,10088.64
Exp/Cntr=0.3,0.1

Type RM Length L Ch R = 1 ,22164.62,134.389100,134.389100,134.389100
XS GIS Cut Line= 2
837314.446662207749878.565582813837120.803338456749763.155995544
#Sta/Elev= 26
9913.122479.99669920.087 476.6079924.119 475.4029935.761474.40479939.619473.3468
9947.402 470.1259970.685459.28879982.326455.29689993.967 454.3359998.218453.6503
10005.61453.703110017.25455.401610028.89458.717110037.28459.674510040.53459.7013
10052.17461.316810075.46463.9414 10087.1465.552610095.88467.449710098.74468.2033
10110.38471.683510115.41473.319310122.02475.705610133.66480.942610134.95481.3222
10138.55481.9242
#Mann= 3 , 0 , 0
9913.122    0.04       09913.122    0.04       010138.55    0.04       0
#XS Ineff= 2 , 0
       0                               0
Bank Sta=9913.122,10138.55
Exp/Cntr=0.3,0.1

Type RM Length L Ch R = 1 ,22030.23,91.428600,91.428600,91.428600
XS GIS Cut Line= 2
837354.571655461749682.001707159837124.110222177749742.056406244
#Sta/Elev= 25
9899.798477.21159909.689473.00349920.023466.56939930.357465.29199940.691466.0902
9951.025462.63599961.359459.79969971.693457.12839982.027451.33049991.002443.7774
9992.361442.718810002.69442.427110013.03443.227410023.36446.6738 10033.7454.3521
10044.03462.951310054.36469.0385 10064.7470.404510075.03470.571110085.37472.0195
 10095.7475.465510106.03478.272410116.37 479.679 10126.7 480.51910137.96481.9578
#Mann= 3 , 0 , 0
9899.798  0.0413       09899.798  0.0413       010137.96  0.0413       0
#XS Ineff= 2 , 0
       09960.836                       0
Bank Sta=9899.798,10137.96
Exp/Cntr=0.3,0.1

Type RM Length L Ch R = 3 ,21987.74,,,
BEGIN DESCRIPTION:
END DESCRIPTION:
Bridge Culvert--1,0,-1,-1, 0
Deck Dist Width WeirC Skew NumUp NumDn MinLoCord MaxHiCord MaxSubmerge Is_Ogee
25.714300,40.000000,2.6,0, 26, 26, , , 0.95, 0, 0,0,,
 9934.02 9934.33 9944.71 9955.10 9962.09 9965.49 9975.87 9979.63 9979.63 9986.26
 9996.64 9999.1210007.0310017.4210027.8010029.6310029.6310036.1510038.1910048.57
10058.9610069.3410073.1910079.7310090.1210091.03
  459.85  459.87  460.49  461.18  461.65  461.80  462.45  462.72  462.72  463.20
  464.00  464.18  464.66  465.39  466.13  466.28  466.28  466.80  466.92  467.73
  468.50  469.30  469.60  470.02  470.78  470.86
 -540.15 -540.13 -539.51 -538.82 -538.35 -538.20 -537.55 -537.28  459.72  460.20
  461.00  461.18  461.66  462.39  463.13  463.28 -533.72 -533.20 -533.08 -532.27
 -531.50 -530.70 -530.40 -529.98 -529.22 -529.14
 9934.02 9934.33 9944.71 9955.10 9960.50 9960.50 9962.09 9965.49 9975.87 9986.26
 9996.64 9999.1210007.0310010.5010010.5010017.4210027.8010036.1510038.1910048.57
10058.9610069.3410073.1910079.7310090.1210091.03
  459.85  459.87  460.49  461.18  461.55  461.55  461.65  461.80  462.45  463.20
  464.00  464.18  464.66  464.91  464.91  465.39  466.13  466.80  466.92  467.73
  468.50  469.30  469.60  470.02  470.78  470.86
 -540.15 -540.13 -539.51 -538.82 -538.45  458.55  458.65  458.80  459.45  460.20
  461.00  461.18  461.66  461.91 -535.09 -534.61 -533.87 -533.20 -533.08 -532.27
 -531.50 -530.70 -530.40 -529.98 -529.22 -529.14
BR Coef=-1 , 0 , 0 ,, 0 ,,,0.8,0,1,0,
WSPro=,,,, 1 ,,,, 0 ,,,, 0 ,,,,-1 ,-1 ,-1 , 0 , 0 , 0 , 0 , 0
BC Design=,, 0 ,, 0 ,,,,,,

Type RM Length L Ch R = 1 , 21938.8,112.399100,112.399100,112.399100
XS GIS Cut Line= 2
837340.278215608749599.919126224837094.395597363749643.732634218
#Sta/Elev= 25
9903.964457.75539909.325 457.875 9929.64  457.799932.927456.98759939.798455.7434
9949.955451.99559960.113448.8528 9970.27446.69869980.428444.64769990.585 442.345
10000.74442.3529 10010.9442.608810021.06451.933210031.22459.288410041.37463.3964
10051.53468.507510061.69477.985710071.85477.8486   10082477.882510102.32478.8534
10112.48479.235610132.79479.197810142.95 480.19210153.11483.578110153.72483.9204
#Mann= 3 , 0 , 0
9903.964  0.0449       09903.964  0.0449       010153.72  0.0449       0
#XS Ineff= 2 , 0
       09907.185                       0
Bank Sta=9903.964,10153.72
Exp/Cntr=0.3,0.1

Type RM Length L Ch R = 1 , 21826.4,72.610100,72.610100,72.610100
XS GIS Cut Line= 2
837363.889574218749598.345559941837263.226331234749467.740927769
#Sta/Elev= 25
9929.902457.04639934.126457.29239944.464457.06369946.751457.02699959.377 455.056
9960.844 454.7629972.002453.55099977.225450.96999984.628444.37459993.606439.9747
9997.253439.416210009.88 439.35710009.99439.4078 10022.5446.815710026.37 448.683
10035.13452.661910042.75456.652810047.76 459.19110059.13463.988910060.38464.5429
10073.01470.154310075.51471.301810085.63475.924310091.89478.5294 10094.8479.6763
#Mann= 3 , 0 , 0
9929.902    0.12       09929.902    0.12       0 10094.8    0.12       0
#XS Ineff= 2 , 0
       09936.101                       0
Bank Sta=9929.902,10094.8
Exp/Cntr=0.3,0.1

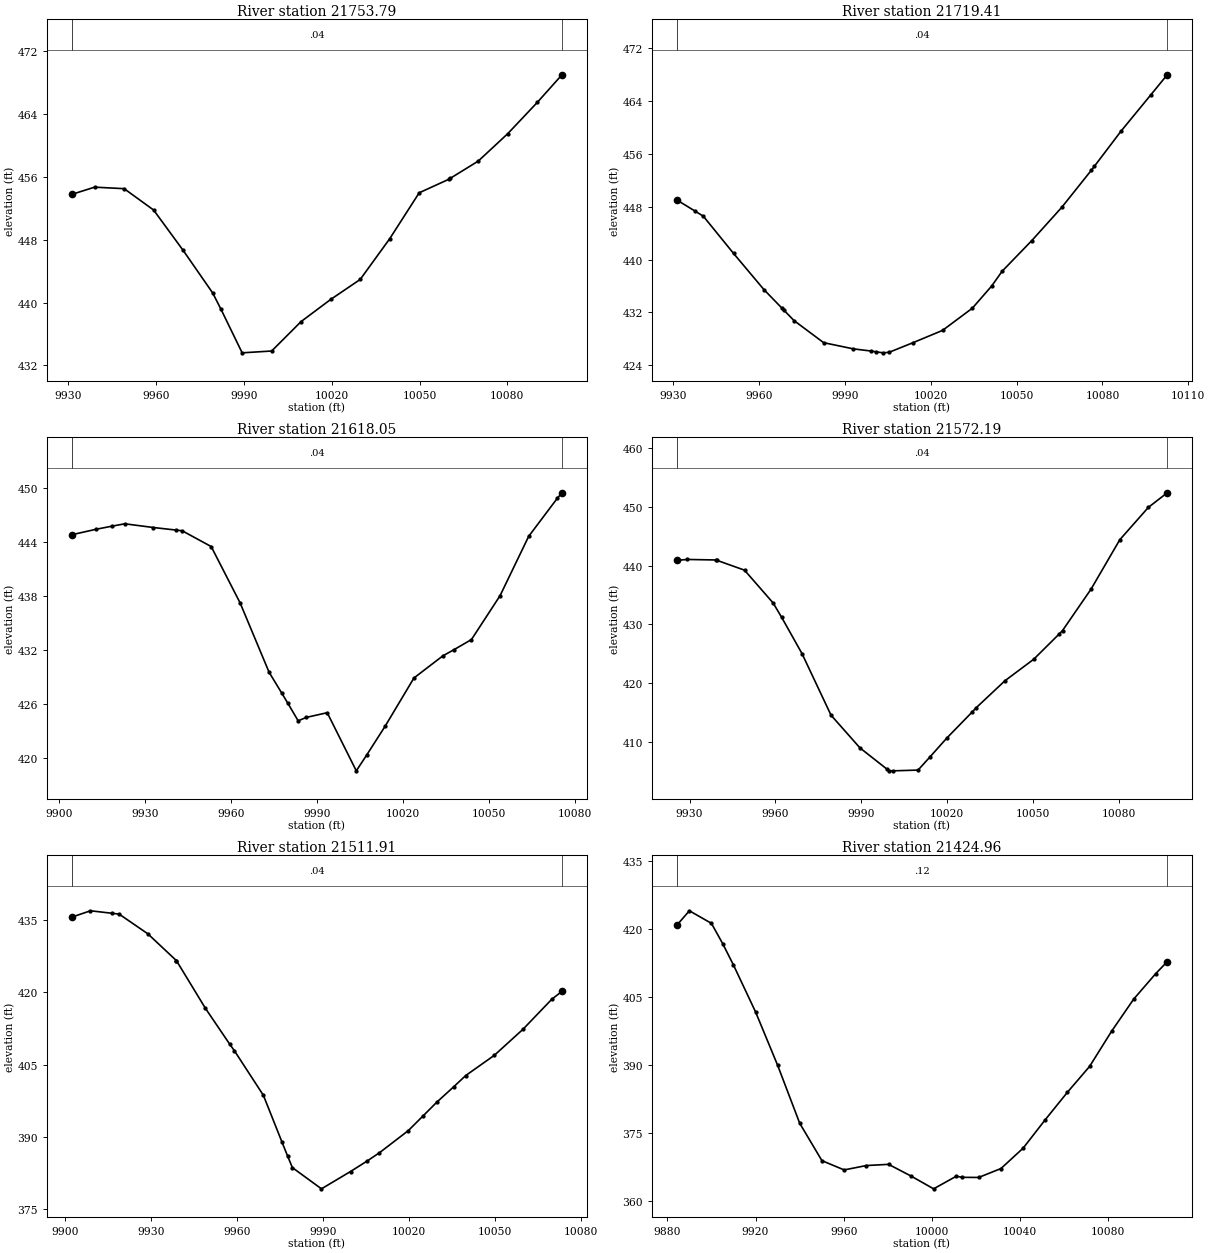
Type RM Length L Ch R = 1 ,21753.79,34.377400,34.377400,34.377400
XS GIS Cut Line= 2
837401.510414327749602.839052847837380.139047282 749436.61082639
#Sta/Elev= 20
9931.064  453.769938.967454.6892 9949.05454.49679959.132451.77479969.214446.6387
9979.296441.22269982.119439.15929989.379433.59349999.461433.826910009.54 437.581
10019.63440.392510029.71442.938110039.79448.119510049.87453.972410059.95455.6846
10060.54455.824710070.04458.005510080.12461.4952 10090.2465.470910098.66468.9982
#Mann= 3 , 0 , 0
9931.064    0.04       09931.064    0.04       010098.66    0.04       0
#XS Ineff= 2 , 0
       0                               0
Bank Sta=9931.064,10098.66
Exp/Cntr=0.3,0.1

Type RM Length L Ch R = 1 ,21719.41,101.365000,101.365000,101.365000
XS GIS Cut Line= 5
837447.099155314749593.780298862837434.828688172749558.452757621
837426.650042142749529.136222063837426.231744763749527.180454336
837397.900258478749429.552904418
#Sta/Elev= 26
9931.166449.04279937.564447.35069940.461446.57349951.047440.92699961.633435.4633
9968.042432.60369968.564432.37159972.149430.7703 9982.53427.41429992.912426.4779
    9999426.1538   10001426.022910003.27425.875310005.42 425.95710013.68427.3968
 10024.1429.275210034.51 432.634 10041.3436.012210044.92438.230110055.33442.8918
10065.75447.902710076.16453.554910077.18454.131110086.57459.494910096.98 464.988
10102.66     468
#Mann= 3 , 0 , 0
9931.166    0.04       09931.166    0.04       010102.66    0.04       0
#XS Ineff= 2 , 0
       0                               0
Bank Sta=9931.166,10102.66
Exp/Cntr=0.3,0.1

Type RM Length L Ch R = 1 ,21618.05,45.860600,45.860600,45.860600
XS GIS Cut Line= 6
837507.164740892749583.608087155 837506.71364476 749569.44339395
837507.852386758749546.985919558837518.649271632749481.375555977
837521.841134445749451.113274466837522.316582123 749413.37611523
#Sta/Elev= 26
9904.212444.77289912.825445.38769918.384445.73199922.833445.99319932.846445.5798
9940.871445.2916 9942.88 445.217    9953443.4722 9963.12437.2163 9973.24 429.533
9977.696 427.2059979.696426.15079983.385424.15689986.172424.53069993.536425.0574
10003.69418.613810007.37420.387510013.78423.566610023.83428.904110033.89431.3487
 10037.8432.037610043.91433.160910053.91 438.02510063.91444.602510073.91 448.821
10075.54449.4301
#Mann= 3 , 0 , 0
9904.212    0.04       09904.212    0.04       010075.54    0.04       0
#XS Ineff= 2 , 0
       0                               0
Bank Sta=9904.212,10075.54
Exp/Cntr=0.3,0.1

Type RM Length L Ch R = 1 ,21572.19,60.280100,60.280100,60.280100
XS GIS Cut Line= 6
837556.071994974749568.651851204837555.620909624 749554.48715432
837556.759669148749532.029675528837567.556606998749466.419304883
837570.748493822749436.157018715837571.223970609749398.419851033
#Sta/Elev= 26
9925.516440.8863 9929.17441.04879939.175440.95979939.688440.87489949.188439.2229
9959.201433.61689962.175 431.1669969.289424.97719979.408414.49619989.528408.9144
    9999405.28089999.652405.0287   10001405.011510009.81405.138810013.82407.3066
10019.96410.658210028.67415.0213 10030.1415.764310040.15420.367610050.21424.0348
 10059.1428.341810060.26428.924210070.26436.013910080.26444.400310090.26449.9305
10096.84452.4153
#Mann= 3 , 0 , 0
9925.516    0.04       09925.516    0.04       010096.84    0.04       0
#XS Ineff= 2 , 0
       0                               0
Bank Sta=9925.516,10096.84
Exp/Cntr=0.3,0.1

Type RM Length L Ch R = 1 ,21511.91,86.945500,86.945500,86.945500
XS GIS Cut Line= 6
837611.445841604749601.626592812837610.994768838749587.461902748
837612.133547362 749565.00443641837622.930536874749499.394108616
837626.122448446749469.131840671837626.597957899749431.394692606
#Sta/Elev= 27
9902.192435.55319908.822436.89189916.363436.37329918.829436.20139928.841432.1202
 9938.85426.54229938.854426.53949948.974416.6542 9957.53409.15369959.094407.8569
9969.214398.61659975.675388.96839977.675386.01419979.352383.60649989.504379.2073
9999.655382.800710005.35384.936110009.76386.694910019.82391.275710025.08394.3851
10029.88397.234210035.78400.422710039.91402.716610049.91406.917610059.91412.3154
10069.91418.507110073.52420.1855
#Mann= 3 , 0 , 0
9902.192    0.04       09902.192    0.04       010073.52    0.04       0
#XS Ineff= 2 , 0
       0                               0
Bank Sta=9902.192,10073.52
Exp/Cntr=0.3,0.1

Type RM Length L Ch R = 1 ,21424.96,147.225600,147.225600,147.225600
XS GIS Cut Line= 6
837698.202677971749620.723429695837699.812115332749565.038740277
 837704.78829114 749523.51647939837711.766194966749492.268941512
837715.788250118749465.082642793837719.068710584749399.809482233
#Sta/Elev= 26
9884.267420.77659889.991423.97679899.992421.21029905.103416.74039909.999412.0221
9920.014 401.7029930.029389.94529940.044377.17049950.116368.94319960.187366.9054
9970.259367.86989980.331368.13489990.524365.558710000.77362.739810011.04365.5151
10013.85365.2734 10021.2365.245610031.31 367.21210041.33371.679610051.44377.9874
10061.47384.0189 10071.5389.693610081.53397.477410091.53404.536210101.53410.1496
10106.72412.7725
#Mann= 3 , 0 , 0
9884.267    0.12       09884.267    0.12       010106.72    0.12       0
#XS Ineff= 2 , 0
       0                               0
Bank Sta=9884.267,10106.72
Exp/Cntr=0.3,0.1