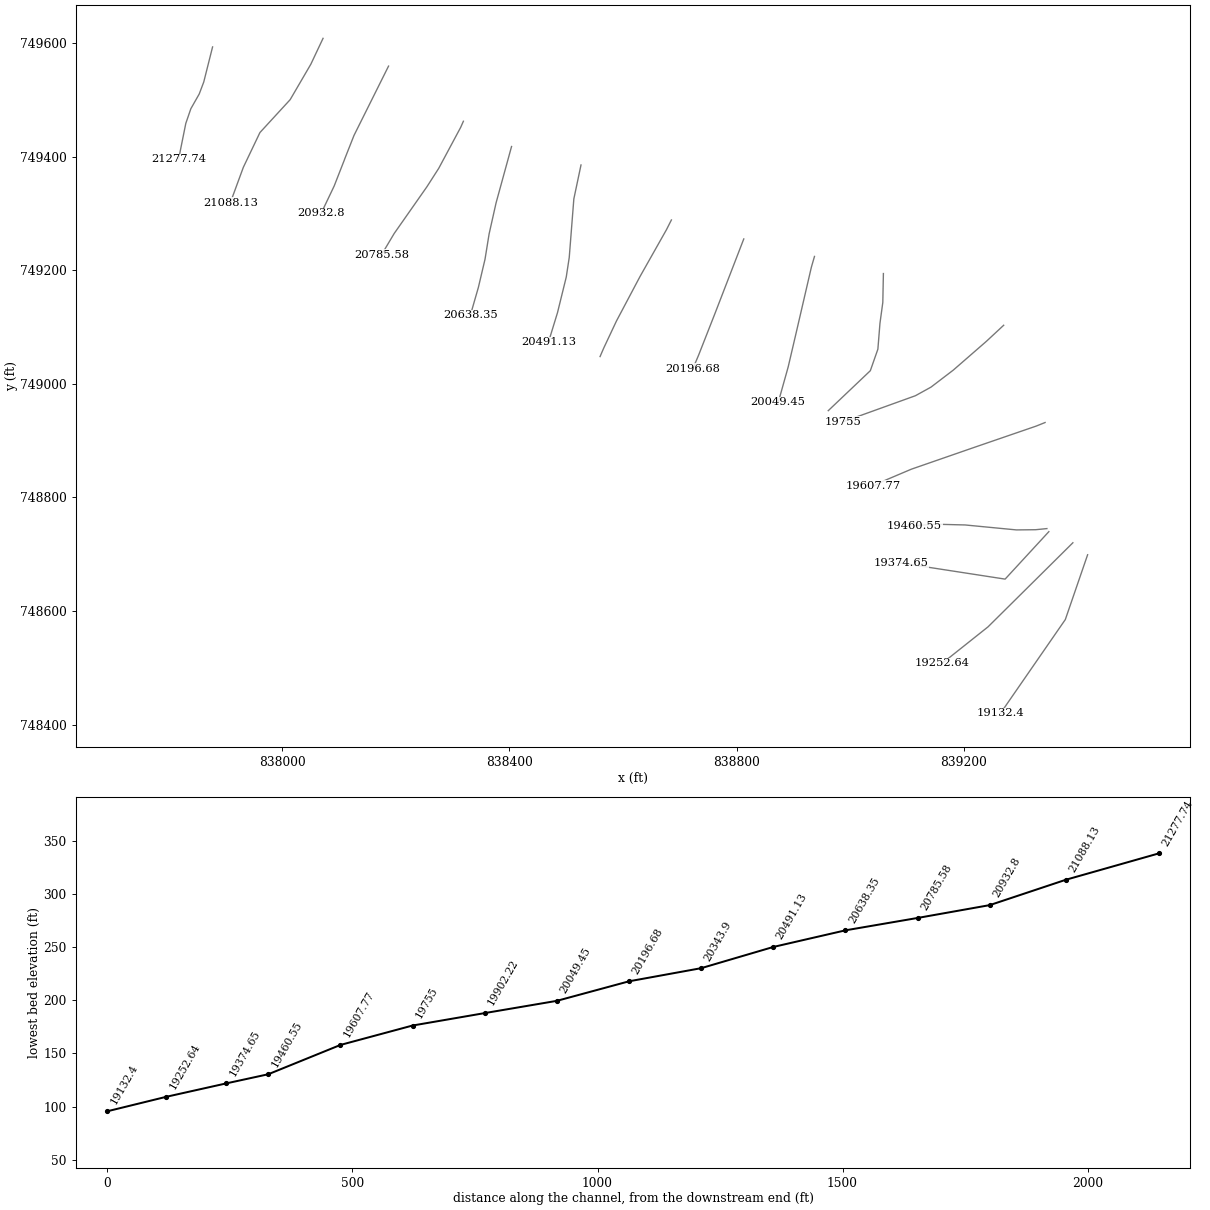
HEC-RAS study 8524_ras.prj: 8524

--- 8524_ras.g01 (geometry) --- (continued)

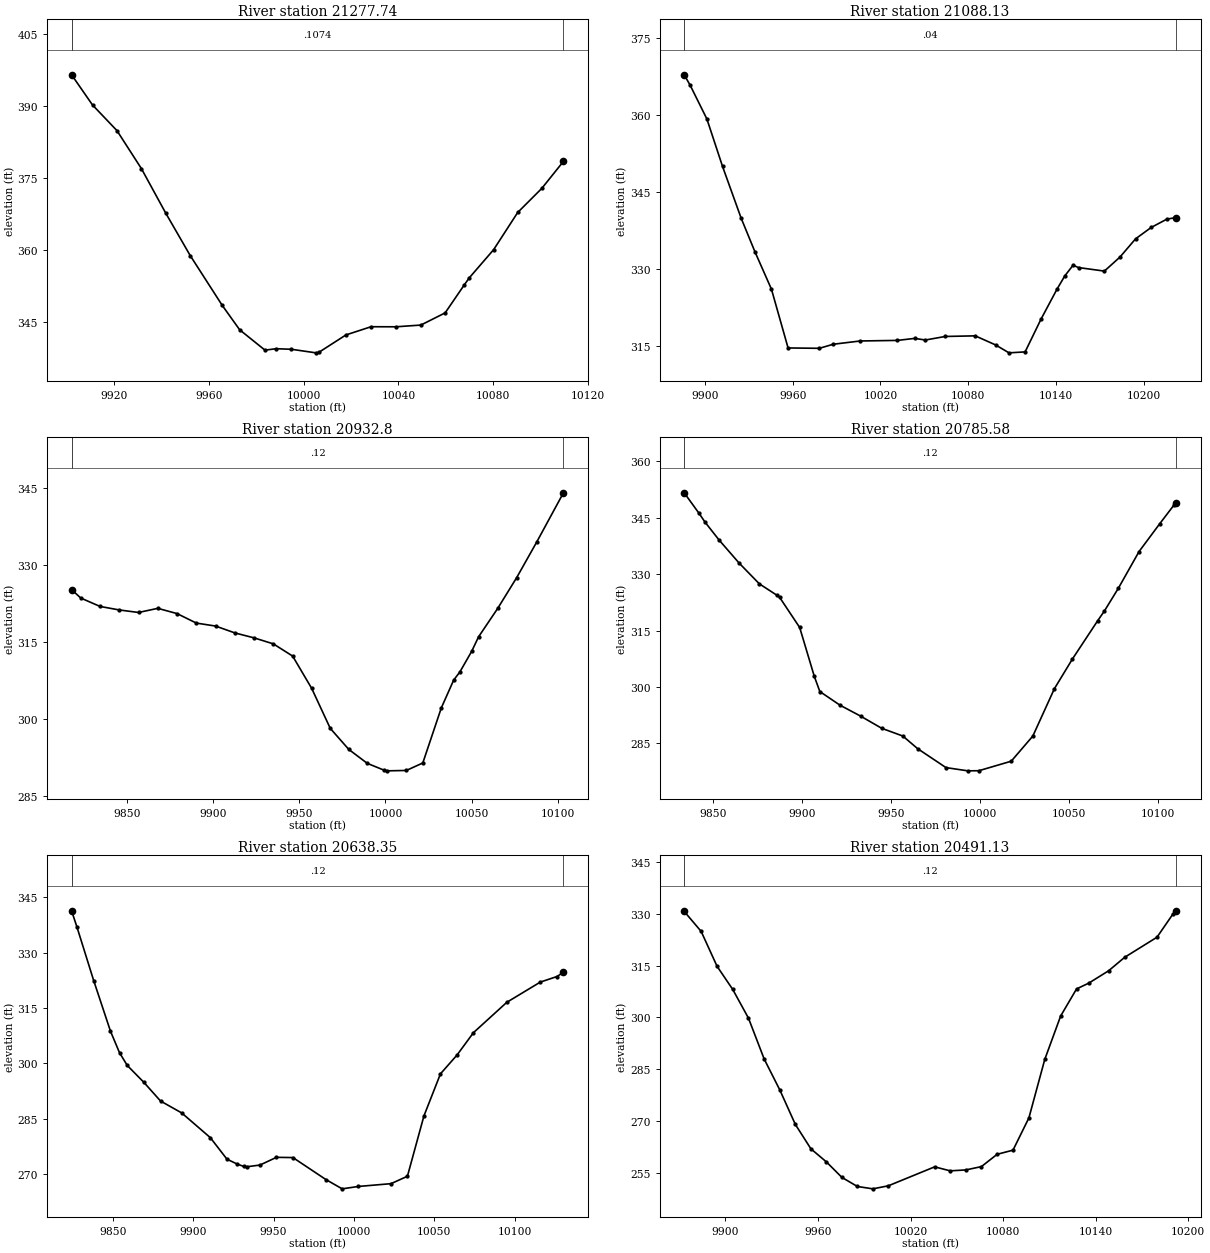
Type RM Length L Ch R = 1 ,21277.74,189.606400,189.606400,189.606400
XS GIS Cut Line= 6
837877.040960125749593.576135261 837861.53002377   749531.889554
837853.500828768749510.614508927837838.784945704749484.753915712
837829.906101191749458.933691499837817.229713491749395.982726848
#Sta/Elev= 24
9901.997396.4555 9910.84390.16189921.151 384.8299931.463 376.9239941.774367.6172
9952.085358.79799965.604348.41699972.968343.33649983.656339.09599988.344339.3987
9994.834339.277710005.14338.537910006.44338.659210017.83342.269210028.43343.9759
   10039343.962910049.45344.3227 10059.7346.857610067.83 352.72410069.95354.1906
10080.19360.036810090.34367.778410100.49372.781610109.65378.4171
#Mann= 3 , 0 , 0
9901.997  0.1074       09901.997  0.1074       010109.65  0.1074       0
#XS Ineff= 2 , 0
       0                               0
Bank Sta=9901.997,10109.65
Exp/Cntr=0.3,0.1

Type RM Length L Ch R = 1 ,21088.13,155.326100,155.326100,155.326100
XS GIS Cut Line= 6
838071.624113652749608.713814108838050.114082388749563.150613885
838013.729185092749500.753014115837960.450332116 749442.77926095
837931.248574278749381.591770572 837908.25976301749318.990398454
#Sta/Elev= 30
9885.799367.76449889.906365.71639901.316359.17799912.023349.9485 9924.74339.8911
 9934.14333.38089945.454326.08879956.826314.66379978.212314.5953 9987.64315.3813
10006.12316.020810031.53316.132110043.39316.5212 10050.7316.207810064.25316.8978
10084.76317.017510098.69315.251310107.84313.714710118.86313.896410129.79 320.293
10140.71326.115110146.03328.681510151.63330.743310155.36330.290210173.06329.6036
10183.72332.336510194.39335.880510205.05338.088410215.72 339.69510222.05340.0152
#Mann= 3 , 0 , 0
9885.799    0.04       09885.799    0.04       010222.05    0.04       0
#XS Ineff= 2 , 0
       0                10059.29       0
Bank Sta=9885.799,10222.05
Exp/Cntr=0.3,0.1

Type RM Length L Ch R = 1 , 20932.8,147.225600,147.225600,147.225600
XS GIS Cut Line= 6
838186.967184531749559.770161563838126.078408435749437.588395999
838109.706797921749396.143197954838109.053776132749394.252811105
838091.204066754749348.598595267838068.299754529749300.550031195
#Sta/Elev= 30
9817.925325.11489823.255323.47269834.428321.83799845.601321.15159856.774320.6593
9867.947321.4654 9879.12320.44279890.293318.59399901.466318.01389912.639316.6796
9923.812315.71179934.985314.54269946.157312.16639957.221305.86599967.973298.0901
9978.725 293.9879989.477 291.267    9999289.9679   10001 289.81310012.13289.8857
10021.67291.349110032.41302.0804 10039.6307.507210043.15309.063610050.02313.0912
10054.01315.917510065.08321.434810076.16327.471910087.68334.343410103.25343.9754
#Mann= 3 , 0 , 0
9817.925    0.12       09817.925    0.12       010103.25    0.12       0
#XS Ineff= 2 , 0
       0                               0
Bank Sta=9817.925,10103.25
Exp/Cntr=0.3,0.1

Type RM Length L Ch R = 1 ,20785.58,147.225600,147.225600,147.225600
XS GIS Cut Line= 6
838318.789799811 749462.67663567838314.041065237749451.952889592
838275.353371989749379.734946138838254.689459075749347.490952897
838196.905771369  749264.9716808838174.346831792749227.089879623
#Sta/Elev= 30
9833.556351.59329841.952346.10969845.284343.80049853.172 339.053 9864.43332.9378
9875.861327.39599885.607324.40929887.206  323.85 9898.55 315.8039906.784302.8048
9909.895298.78449921.239295.15729932.836292.25569944.713289.01839956.591286.9612
9964.934283.60389980.869278.57699993.165277.71519999.337277.742910017.59280.2746
10029.75286.9593 10041.9299.559410052.02307.425710066.25317.609610069.98320.1553
10077.86326.219710089.52335.978910101.14343.359510109.07348.271610110.34348.9865
#Mann= 3 , 0 , 0
9833.556    0.12       09833.556    0.12       010110.34    0.12       0
#XS Ineff= 2 , 0
       0                               0
Bank Sta=9833.556,10110.34
Exp/Cntr=0.3,0.1

Type RM Length L Ch R = 1 ,20638.35,147.225600,147.225600,147.225600
XS GIS Cut Line= 6
838403.627175521749418.170509388838376.389557595749318.996009514
838364.091343206 749264.19139513838356.894550162749219.635714776
838345.195648267749170.025081637838331.129896653749121.155192772
#Sta/Elev= 30
9824.349341.33669827.661336.98999838.108322.43669848.554308.72879854.175302.9048
9859.001299.45469869.366 294.8679879.695289.82649892.853286.60689910.684279.9042
9921.013274.08369927.215272.79559931.311272.13619933.562272.03449941.559272.4912
9951.808274.58159962.057274.51489982.554268.57299992.684266.050310002.79 266.697
10023.08267.450410033.28269.458410043.56285.793310053.83297.183710064.11302.2631
10074.38308.342310095.13316.562210115.94322.023310126.35 323.53910130.35324.7101
#Mann= 3 , 0 , 0
9824.349    0.12       09824.349    0.12       010130.35    0.12       0
#XS Ineff= 2 , 0
       0                               0
Bank Sta=9824.349,10130.35
Exp/Cntr=0.3,0.1

Type RM Length L Ch R = 1 ,20491.13,147.225600,147.225600,147.225600
XS GIS Cut Line= 6
838525.945278417749385.658525899838513.327786351 749325.84143001
838505.231049287749222.772100915838499.961062132749188.234142319
838484.584415419749125.662486726838468.497358838749073.181395188
#Sta/Elev= 30
9873.248330.67689884.244324.89089894.561314.78859904.741308.07559914.916299.7858
 9925.09287.96149935.256278.98379945.324269.01229955.392261.9609 9965.46  258.17
9975.484253.68959985.506 251.0699995.528250.381910005.56251.2563 10035.6256.7459
10045.69255.590310055.81255.852710065.93256.8203 10076.1260.3761 10086.4261.5785
 10096.7270.912110106.99287.846410117.29300.401610127.59308.238810135.46 309.903
10148.36313.482610158.81317.397510179.73323.200310190.19329.984210192.09330.8522
#Mann= 3 , 0 , 0
9873.248    0.12       09873.248    0.12       010192.09    0.12       0
#XS Ineff= 2 , 0
       0                               0
Bank Sta=9873.248,10192.09
Exp/Cntr=0.3,0.1

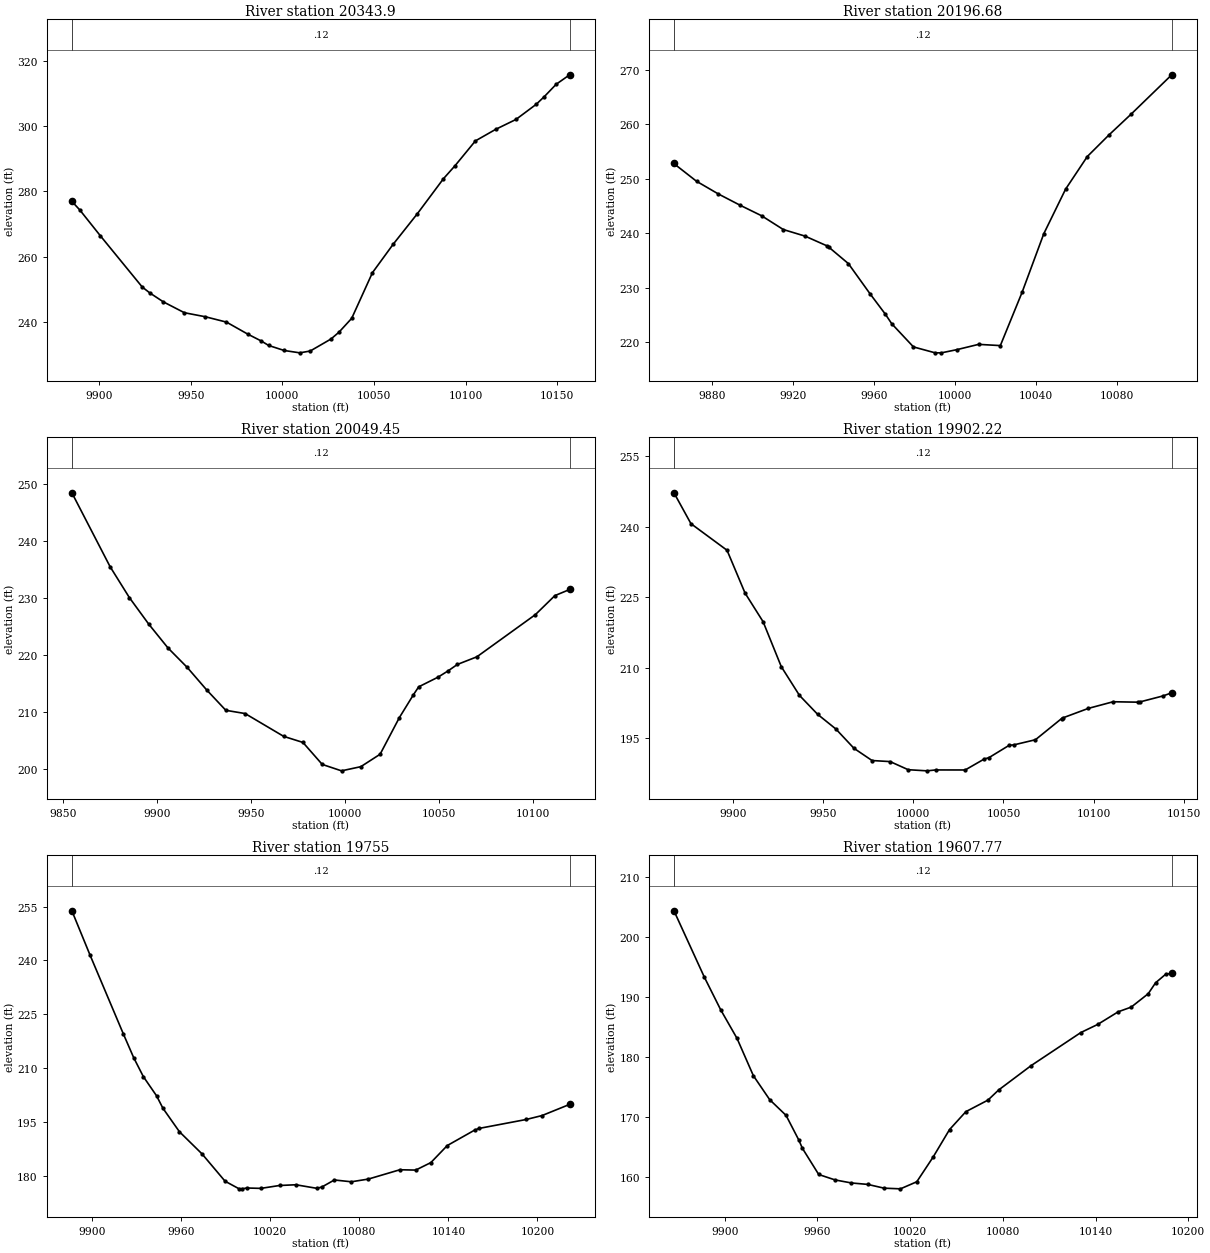
Type RM Length L Ch R = 1 , 20343.9,147.225600,147.225600,147.225600
XS GIS Cut Line= 6
838685.157141793749288.828534142838676.387644822749271.535764586
838629.941179492749189.318122458838588.352325897749110.782695143
838565.792775344749062.787577673 838559.52942674749048.235493588
#Sta/Elev= 30
 9885.18276.94819889.473274.33449900.685266.39959923.569250.62479927.692248.8103
9935.059246.0708 9946.55242.7256 9958.04  241.48 9969.53239.8347 9981.02236.1801
9988.605233.9991 9992.51232.6617   10001231.113210009.52230.391210015.21230.9515
10026.53234.6429 10030.9 236.74310037.84241.000910049.15255.038910060.47263.7847
10073.66 273.16610087.87283.912210094.26287.956410105.31295.542510116.36299.0912
10127.41302.130210138.46306.781310142.91309.159510149.38312.954610156.74315.8711
#Mann= 3 , 0 , 0
 9885.18    0.12       0 9885.18    0.12       010156.74    0.12       0
#XS Ineff= 2 , 0
       0                               0
Bank Sta=9885.18,10156.74
Exp/Cntr=0.3,0.1

Type RM Length L Ch R = 1 ,20196.68,147.225500,147.225500,147.225500
XS GIS Cut Line= 5
838812.626829788749255.398906275838762.899830283749126.673754868
838762.181146091749124.807343038838733.310343309749051.299443166
838722.793055411749026.420889546
#Sta/Elev= 27
9861.004252.89389861.431 252.6719872.152 249.5559882.872247.23369893.592245.1672
9904.312243.21269915.033240.68039925.753239.47449936.473237.7054 9937.67237.3939
9947.193234.41949957.913228.85959965.421225.14159968.634223.35549979.354 219.101
9990.074 218.0159993.172218.014110000.79218.598610011.54219.571510022.28219.3459
10033.02 229.13610043.77239.928910054.51 248.09610065.25254.1016   10076258.0858
10086.81261.859710106.98269.1289
#Mann= 3 , 0 , 0
9861.004    0.12       09861.004    0.12       010106.98    0.12       0
#XS Ineff= 2 , 0
       0                               0
Bank Sta=9861.004,10106.98
Exp/Cntr=0.3,0.1

Type RM Length L Ch R = 1 ,20049.45,147.225600,147.225600,147.225600
XS GIS Cut Line= 6
 838937.16903762749224.569506843838931.649299169749205.463028456
838903.547444587 749084.23662417838890.800218756 749029.76812425
838874.165751616748970.380984949838873.138440072748967.494830874
#Sta/Elev= 25
9854.671248.39159875.034235.4158  9885.3229.99219895.565225.3571 9905.83221.1662
9916.095217.7452 9926.36213.82519936.625210.22299946.891209.65529967.421205.6524
9977.686204.58539987.951200.72999998.216199.602510008.49200.332710018.76202.5137
10029.03208.9529 10036.5212.9546 10039.3214.342510049.57216.034210054.94217.1384
10059.89218.269410070.28219.609710101.43227.012410111.82230.351910119.68231.4214
#Mann= 3 , 0 , 0
9854.671    0.12       09854.671    0.12       010119.68    0.12       0
#XS Ineff= 2 , 0
       0                               0
Bank Sta=9854.671,10119.68
Exp/Cntr=0.3,0.1

Type RM Length L Ch R = 1 ,19902.22,147.225600,147.225600,147.225600
XS GIS Cut Line= 6
839058.554181126749194.430178598839057.512769479749143.606905014
839052.497487675749106.797800035839048.823590333749061.232529872
839035.521777591749023.305228875838961.435966277748952.945722078
#Sta/Elev= 29
9867.302247.24219876.735240.66349896.739235.00639906.741225.88679916.743219.7961
9926.823210.23439936.915204.11169947.008200.07939957.089196.9675 9967.12192.8575
9977.151190.25369987.182190.02799997.213188.2989 10007.6188.059810012.55188.2507
 10028.8188.2427 10039.4190.583810041.91190.849910053.25193.5085 10055.7193.5759
10067.77194.6806 10082.3199.196210083.29199.378910097.08201.348710110.87202.7655
10124.66202.672910125.86202.742210138.45203.997610143.36204.6664
#Mann= 3 , 0 , 0
9867.302    0.12       09867.302    0.12       010143.36    0.12       0
#XS Ineff= 2 , 0
       0                               0
Bank Sta=9867.302,10143.36
Exp/Cntr=0.3,0.1

Type RM Length L Ch R = 1 ,   19755,147.225600,147.225600,147.225600
XS GIS Cut Line= 6
839270.386454354749103.359087503 839239.90484084 749075.03030815
839181.599950653749024.330655377839142.316148588 748994.36009661
839114.889164103748979.230455208838987.493204381748933.330364407
#Sta/Elev= 30
9886.612 253.8579898.891241.45869921.269219.52529928.225212.90529934.686207.6511
9943.635 202.2659947.858198.83249958.999192.26649974.202186.09069989.727178.4671
    9999176.388410000.84176.342210004.54176.574110013.82176.4704 10026.4177.2766
10037.39 177.47810051.56176.479210054.93176.866710063.29 178.81410074.71 178.309
10086.13179.0613 10107.4 181.66410118.03181.568910128.24183.659410139.28188.4072
10157.74192.723810160.54193.174810192.43195.676710203.06196.769910221.67199.8885
#Mann= 3 , 0 , 0
9886.612    0.12       09886.612    0.12       010221.67    0.12       0
#XS Ineff= 2 , 0
       0                               0
Bank Sta=9886.612,10221.67
Exp/Cntr=0.3,0.1

Type RM Length L Ch R = 1 ,19607.77,147.225600,147.225600,147.225600
XS GIS Cut Line= 6
839343.312540526748932.061922904839327.592721944748925.753049727
839218.891723843748888.387181415  839107.7609805748849.855254129
839058.370716381748828.914653143839041.430497886748820.221573717
#Sta/Elev= 30
9867.117204.42199886.798 193.3449897.372187.90449907.946183.13459918.521176.9148
9929.095 172.9129939.669170.29769947.896166.19819950.244164.80769960.818160.4351
9971.392159.53019981.967159.02399992.541 158.78210003.13158.154610013.71 158.043
10024.29159.224510034.88 163.35210045.46167.920610056.04170.914110070.37172.8456
10077.21174.521210098.38178.613210130.48184.114210141.34185.460110154.68187.5776
10163.07 188.35610174.06190.584110178.84192.4124 10185.3193.821510189.31 194.017
#Mann= 3 , 0 , 0
9867.117    0.12       09867.117    0.12       010189.31    0.12       0
#XS Ineff= 2 , 0
       0                               0
Bank Sta=9867.117,10189.31
Exp/Cntr=0.3,0.1

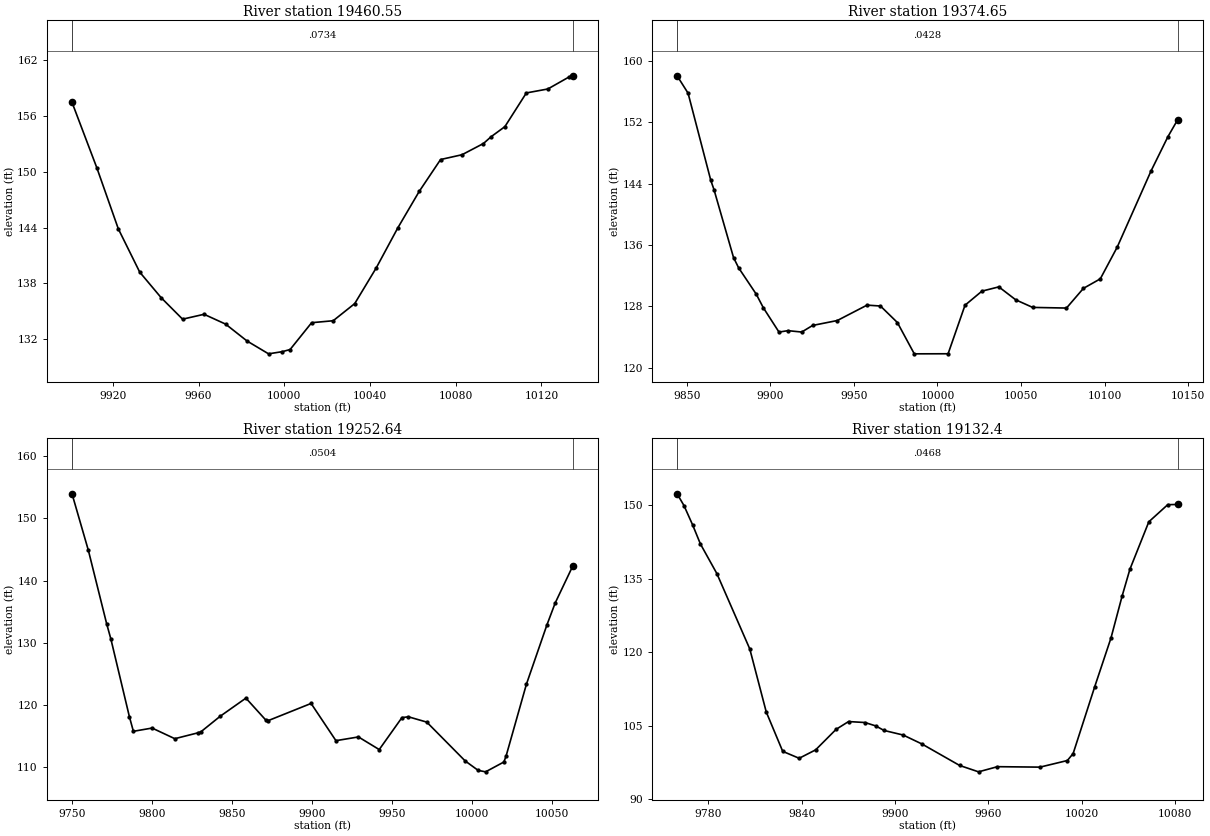
Type RM Length L Ch R = 1 ,19460.55,85.898800,85.898800,85.898800
XS GIS Cut Line= 6
839346.517628785 748745.24836691839326.649838289748743.265062475
839292.863549252748742.910108847839202.381943141748751.646415561
839151.433645071748752.921163792839113.484282404748750.555347253
#Sta/Elev= 27
9900.907157.46269912.482150.43799922.523143.86949932.524139.21589942.525136.4723
9952.525134.16399962.554134.6884 9972.59133.63619982.626131.81679992.662130.4394
    9999 130.67110002.71130.901810012.77133.785610022.82133.995110032.88135.8365
10042.94 139.67910052.95 143.95510062.96147.882510072.96151.316110082.96151.8311
10092.97153.038310096.53153.763610102.98 154.851   10113158.471910123.02158.8955
10133.04160.201710134.56160.3152
#Mann= 3 , 0 , 0
9900.907  0.0734       09900.907  0.0734       010134.56  0.0734       0
#XS Ineff= 2 , 0
       0                               0
Bank Sta=9900.907,10134.56
Exp/Cntr=0.3,0.1

Type RM Length L Ch R = 1 ,19374.65,122.007700,122.007700,122.007700
XS GIS Cut Line= 3
839349.954975496748739.833292206839272.935697883748656.255720626
839089.279052672748684.606357832
#Sta/Elev= 30
9844.197158.0879 9850.77155.81629864.368144.43259866.266143.23779877.967134.3678
9881.022133.02289891.566129.58479895.779127.81999905.164124.64049910.535124.8244
9918.763124.64389925.292125.50489940.048126.14719957.851128.15689965.881128.0403
9975.999125.88779986.118121.799410006.35121.809510016.47128.144110026.59129.9818
10036.71130.538810046.83 128.84710056.95127.858610077.18 127.774 10087.3130.3412
10097.42131.587110107.54135.726510127.78145.668810137.89 150.14510143.68152.3416
#Mann= 3 , 0 , 0
9844.197  0.0428       09844.197  0.0428       010143.68  0.0428       0
#XS Ineff= 2 , 0
       0                               0
Bank Sta=9844.197,10143.68
Exp/Cntr=0.3,0.1

Type RM Length L Ch R = 1 ,19252.64,120.242400,120.242400,120.242400
XS GIS Cut Line= 3
839392.273193613748720.264876253839242.802067956748572.156747166
839162.424094766748508.259823361
#Sta/Elev= 30
9749.976153.97329760.215144.85979771.664133.03279774.293 130.5869785.871 118.082
9788.371115.72899800.078116.25179814.286114.53959828.493 115.4669830.604115.6477
  9842.7118.1566 9858.76121.07059871.115117.56239872.838117.4617 9899.53120.2145
9915.071114.22189929.149 114.8229942.152112.78869956.359117.93249960.399118.0662
  9971.9117.20839995.915110.958810004.04109.437310008.69109.202410020.11 110.784
10021.46111.698210034.24123.321310047.01132.826310052.25136.402510063.08142.2674
#Mann= 3 , 0 , 0
9749.976  0.0504       09749.976  0.0504       010063.08  0.0504       0
#XS Ineff= 2 , 0
       0                               0
Bank Sta=9749.976,10063.08
Exp/Cntr=0.3,0.1

Type RM Length L Ch R = 1 , 19132.4,124.335900,124.335900,124.335900
XS GIS Cut Line= 3
839418.252373631748699.172622717839378.960745923748585.019439631
839264.701921068748419.783287015
#Sta/Elev= 30
 9759.95152.27479764.363149.87829769.943145.92289774.938142.04359785.514135.9994
9806.666120.63279817.242107.78659827.81799.759069838.39398.343519848.969100.0606
 9862.12104.24269870.121105.83319880.676105.6346 9887.64104.93929892.857 104.026
9905.222103.08469917.173101.27669941.48996.883459953.64795.580439965.80596.63219
9993.13396.5403810010.7297.8871210014.4499.31465 10028.3112.937610038.75122.8731
10045.88 131.39110050.91136.886310063.07146.562210075.23150.056110081.57150.0936
#Mann= 3 , 0 , 0
 9759.95  0.0468       0 9759.95  0.0468       010081.57  0.0468       0
#XS Ineff= 2 , 0
       0                               0
Bank Sta=9759.95,10081.57
Exp/Cntr=0.3,0.1