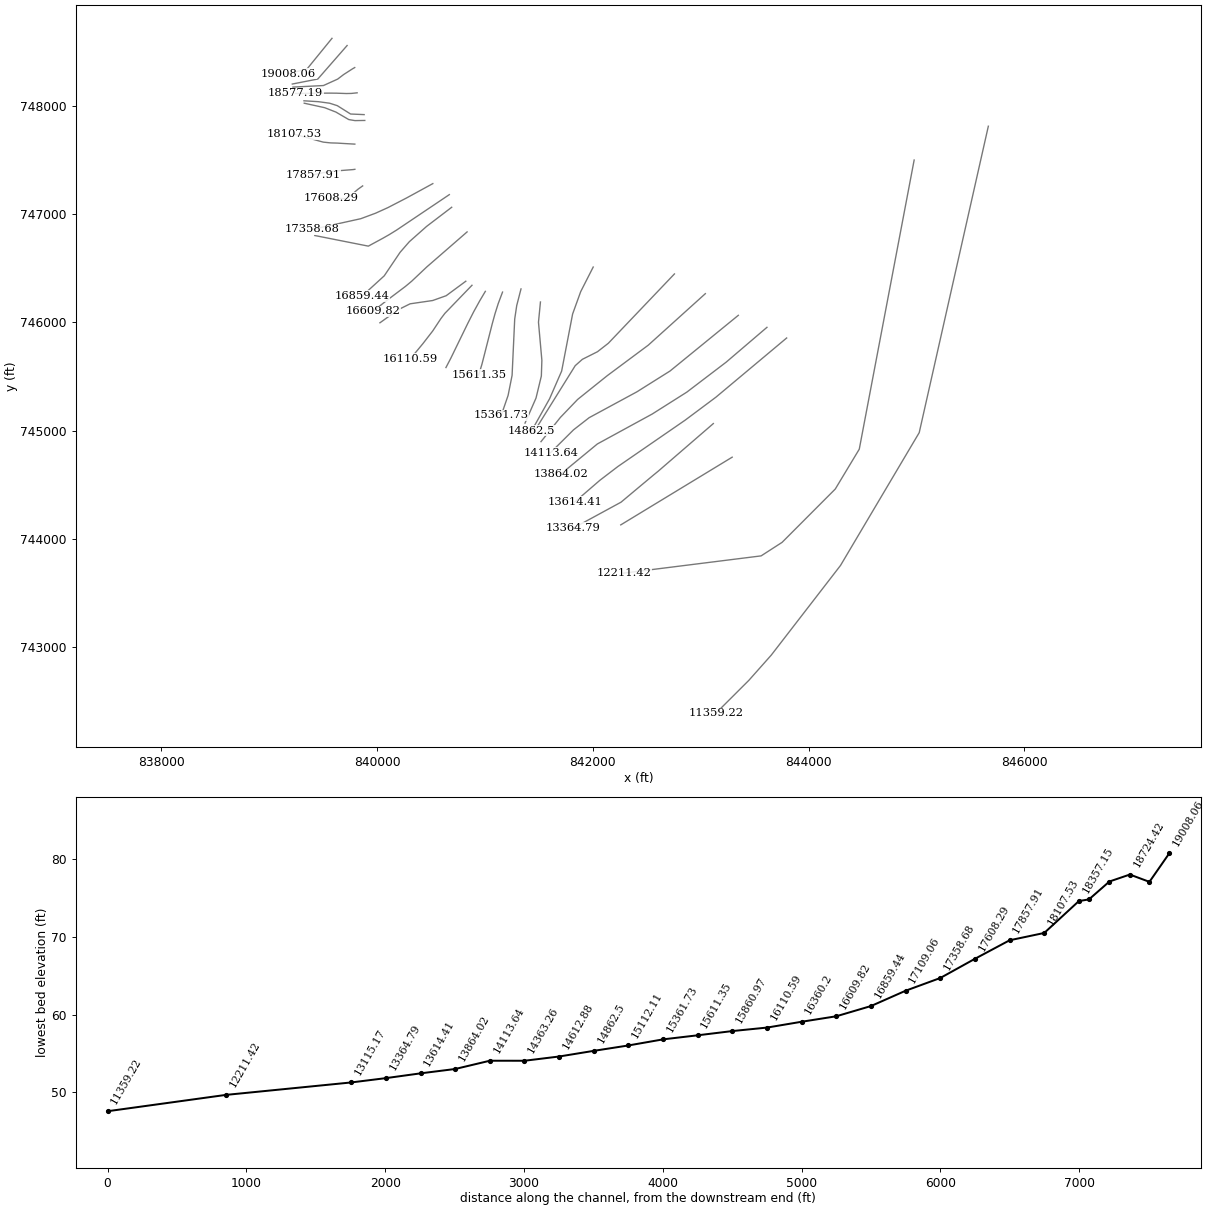
HEC-RAS study 8524_ras.prj: 8524

--- 8524_ras.g01 (geometry) --- (continued)

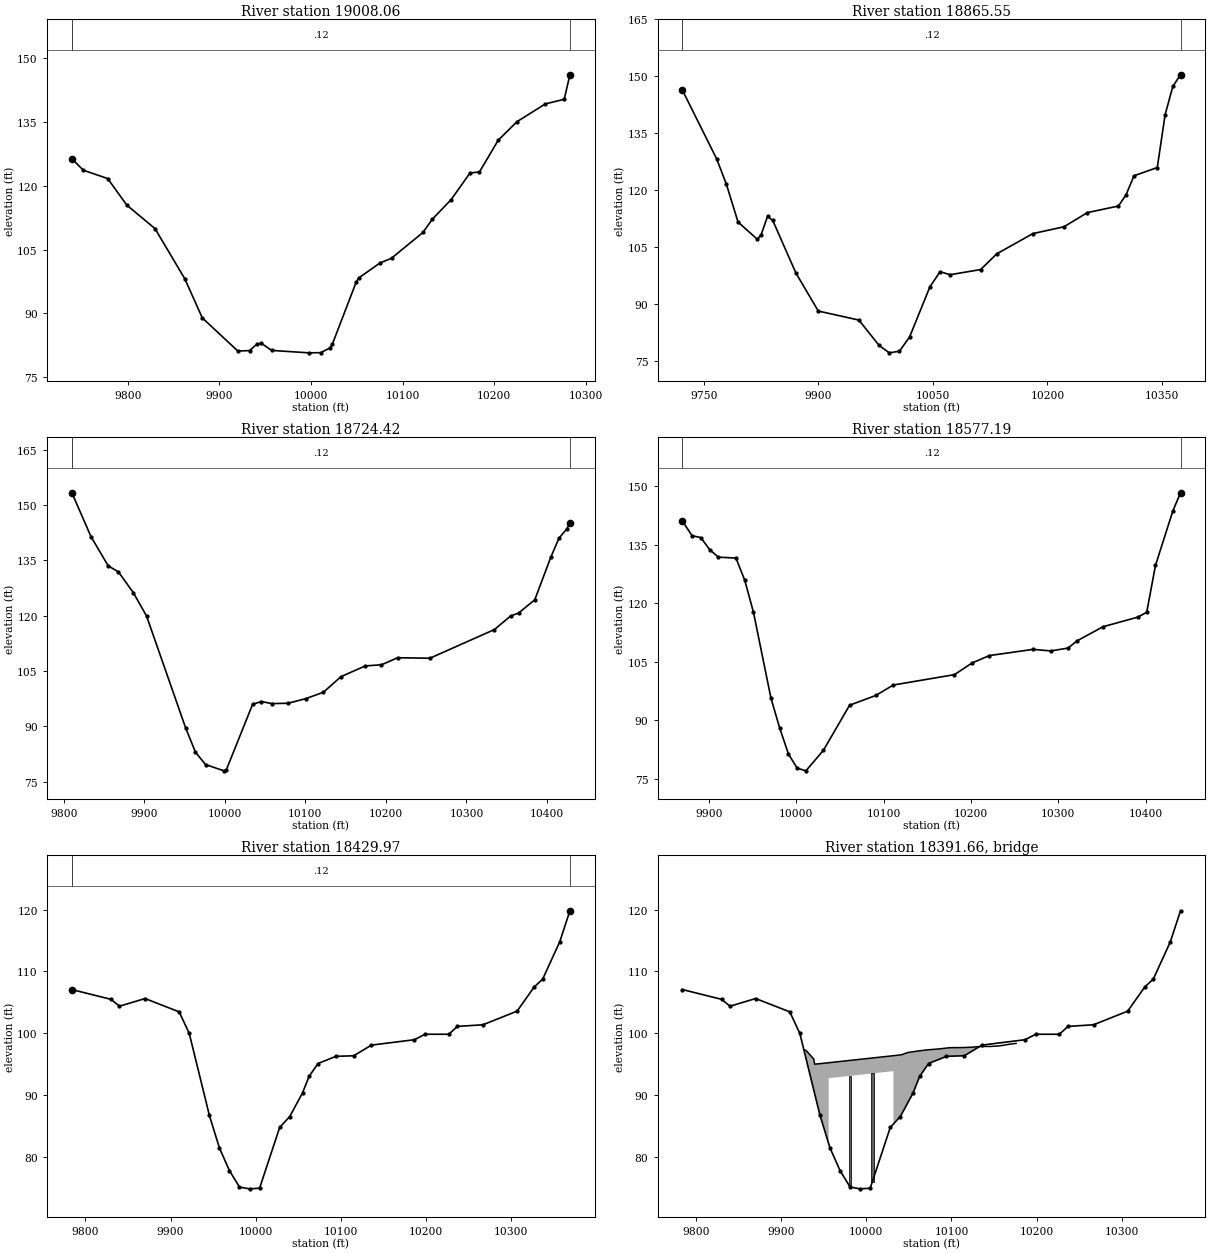
Type RM Length L Ch R = 1 ,19008.06,142.516600,142.516600,142.516600
XS GIS Cut Line= 3
839582.938496801748625.267050307839350.938192191748341.187849904
839178.953981761748300.081120816
#Sta/Elev= 30
9738.951126.33629751.502123.66399778.029121.7016 9798.93115.44949829.674109.9292
9862.16798.132129881.31888.910219920.05181.121279932.96281.220769941.21482.79252
9945.87382.920429957.02381.264589997.51880.6917210010.4380.7335610020.2681.78862
10023.3482.7728110049.1697.2727410051.8898.2779510074.98101.8021 10087.9102.9645
10122.12109.0143 10132.4112.132510152.96116.759310173.52123.020510183.81 123.251
10204.37130.739510224.93135.104510255.78139.267910276.34140.357510282.56146.1225
#Mann= 3 , 0 , 0
9738.951    0.12       09738.951    0.12       010282.56    0.12       0
#XS Ineff= 2 , 0
       0                               0
Bank Sta=9738.951,10282.56
Exp/Cntr=0.3,0.1

Type RM Length L Ch R = 1 ,18865.55,141.126600,141.126600,141.126600
XS GIS Cut Line= 3
 839722.96998625748558.778110238839451.493322652748249.178542364
839215.139823392748202.963550472
#Sta/Elev= 30
9721.894146.29169766.819128.14019779.486121.49069794.654111.54999820.019106.9869
9824.989108.23579833.319113.02369840.157111.96889870.492 98.10339899.81988.07047
9953.019  85.6819979.61978.981329992.91977.0384810006.2277.4773710019.5281.24103
10046.1294.4593910059.42  98.43310072.7297.6503910112.6299.0130610133.66103.1489
10181.03108.501310221.79110.294410252.36114.031310293.12115.768510303.31118.8114
 10313.5 123.75310344.06125.929710354.25139.810110364.44147.352910374.49150.3987
#Mann= 3 , 0 , 0
9721.894    0.12       09721.894    0.12       010374.49    0.12       0
#XS Ineff= 2 , 0
       0                               0
Bank Sta=9721.894,10374.49
Exp/Cntr=0.3,0.1

Type RM Length L Ch R = 1 ,18724.42,147.225600,147.225600,147.225600
XS GIS Cut Line= 6
839793.631249151748355.110676113839772.980733446748343.389121946
839691.541640472748290.981705564839635.604868896748248.596160268
839503.669007035748189.026829458839221.411997741748174.676520136
#Sta/Elev= 30
9810.211153.32619833.956141.42589855.338133.51239867.937 131.9019886.417126.2833
9902.905119.91919951.26189.71389 9963.6383.015299976.15779.68135    9999 77.9774
10001.6678.1077210034.5896.0229710045.5596.7606810058.3496.1945410078.4796.29199
10100.4197.5336810122.3699.26268 10144.3103.511110174.47106.409310194.49106.7164
10214.52 108.62210254.57108.492210334.67116.2633 10354.7119.927310364.71120.7427
10384.74124.318110404.76135.912710414.78141.002810424.79143.611910428.38145.1725
#Mann= 3 , 0 , 0
9810.211    0.12       09810.211    0.12       010428.38    0.12       0
#XS Ineff= 2 , 0
       0                               0
Bank Sta=9810.211,10428.38
Exp/Cntr=0.3,0.1

Type RM Length L Ch R = 1 ,18577.19,147.225600,147.225600,147.225600
XS GIS Cut Line= 6
839815.905795954748121.687291511839762.449749736748116.131798638
839717.222160234748115.185680498839625.866278448748118.320517113
839555.873180825748119.029927822 839246.34486492748115.676773047
#Sta/Elev= 30
 9869.93 141.0789880.895137.38399890.949 136.8779901.002133.79489911.056131.8653
9931.125131.63279941.128125.9864 9951.13 117.7619971.13495.761999981.137 88.0826
 9991.1481.4181310001.1477.7810210011.1577.0819210031.1782.3363710061.1993.91087
10091.1996.4072810111.1999.08554 10181.2101.7473 10201.2104.7254 10221.2106.6379
 10271.2108.2254 10291.2107.8225 10311.2108.5574 10321.2 110.37610351.21114.0333
10391.21116.499310401.21117.744110411.21129.750710431.21143.780310439.87148.3728
#Mann= 3 , 0 , 0
 9869.93    0.12       0 9869.93    0.12       010439.87    0.12       0
#XS Ineff= 2 , 0
       0                               0
Bank Sta=9869.93,10439.87
Exp/Cntr=0.3,0.1

Type RM Length L Ch R = 1 ,18429.97,72.820100,72.820100,72.820100
XS GIS Cut Line= 6
839880.798960751747920.332279671839755.316500176747925.877079614
839632.269046569748002.971526262839560.885713365748025.737936588
839456.509877542748039.876754147839323.096015583748048.024940863
#Sta/Elev= 30
9784.211107.03889830.055105.46629840.065104.34859870.094 105.589 9910.19 103.435
 9921.9999.952419945.59286.706759957.39281.414179969.19377.743799980.99475.07259
9992.79474.7862810004.59   74.89 10028.284.7321710040.0186.4898810055.0290.32177
10062.65 92.977810073.1595.0686310094.1496.2335110115.13 96.325410135.8998.05102
10186.3498.9229410198.9599.8094510226.7199.8079510236.79101.077810266.84 101.343
10306.92103.547710326.96107.460410336.97108.731910357.01114.778610368.94119.7954
#Mann= 3 , 0 , 0
9784.211    0.12       09784.211    0.12       010368.94    0.12       0
#XS Ineff= 2 , 0
       0                               0
Bank Sta=9784.211,10368.94
Exp/Cntr=0.3,0.1

Type RM Length L Ch R = 3 ,18391.66,,,
BEGIN DESCRIPTION:
END DESCRIPTION:
Bridge Culvert--1,0,-1,-1, 0
Deck Dist Width WeirC Skew NumUp NumDn MinLoCord MaxHiCord MaxSubmerge Is_Ogee
24.910050,23.000000,2.6,0, 29, 29, , , 0.95, 0, 0,0,,
 9926.93 9929.17 9938.26 9939.39 9955.87 9955.8710031.8710031.8710041.1210048.60
10049.8310050.3210059.7610070.8010073.9210081.8410092.8810097.5110102.9410103.87
10114.3810124.8910127.9710135.4010145.9110156.4210160.4710166.9310175.88
   97.28   97.20   95.82   94.96   95.20   95.20   96.34   96.34   96.48   96.85
   96.87   96.88   97.08   97.27   97.31   97.39   97.55   97.63   97.65   97.64
   97.66   97.72   97.77   97.84   97.83   97.93   98.02   98.17   98.33
 -902.72 -902.80 -904.18 -905.04 -904.80   92.70   93.84 -903.66 -903.52 -903.15
 -903.13 -903.12 -902.92 -902.73 -902.69 -902.61 -902.45 -902.37 -902.35 -902.36
 -902.34 -902.28 -902.23 -902.16 -902.17 -902.07 -901.98 -901.83 -901.67
 9926.93 9929.17 9938.26 9939.39 9963.34 9963.3410039.3410039.3410041.1210048.60
10049.8310050.3210059.7610070.8010073.9210081.8410092.8810097.5110102.9410103.87
10114.3810124.8910127.9710135.4010145.9110156.4210160.4710166.9310175.88
   97.28   97.20   95.82   94.96   95.32   95.32   96.45   96.45   96.48   96.85
   96.87   96.88   97.08   97.27   97.31   97.39   97.55   97.63   97.65   97.64
   97.66   97.72   97.77   97.84   97.83   97.93   98.02   98.17   98.33
 -902.72 -902.80 -904.18 -905.04 -904.68   92.82   93.95 -903.55 -903.52 -903.15
 -903.13 -903.12 -902.92 -902.73 -902.69 -902.61 -902.45 -902.37 -902.35 -902.36
 -902.34 -902.28 -902.23 -902.16 -902.17 -902.07 -901.98 -901.83 -901.67
Pier Skew, UpSta & Num, DnSta & Num=  ,9980.70, 2 ,9988.18, 2 , 0 , 0 , 0 ,,
    3.00    3.00
 -904.42   95.58
    3.00    3.00
 -904.31   95.69
Pier Skew, UpSta & Num, DnSta & Num=  ,10007.03, 2 ,10014.51, 2 , 0 , 0 , 0 ,,
    3.00    3.00
 -904.03   95.97
    3.00    3.00
 -903.92   96.08
BR Coef=-1 , 0 , 0 ,, 0 ,,,0.8,0,1,0,
WSPro=,,,, 1 ,,,, 0 ,,,, 0 ,,,,-1 ,-1 ,-1 , 0 , 0 , 0 , 0 , 0
BC Design=,, 0 ,, 0 ,,,,,,

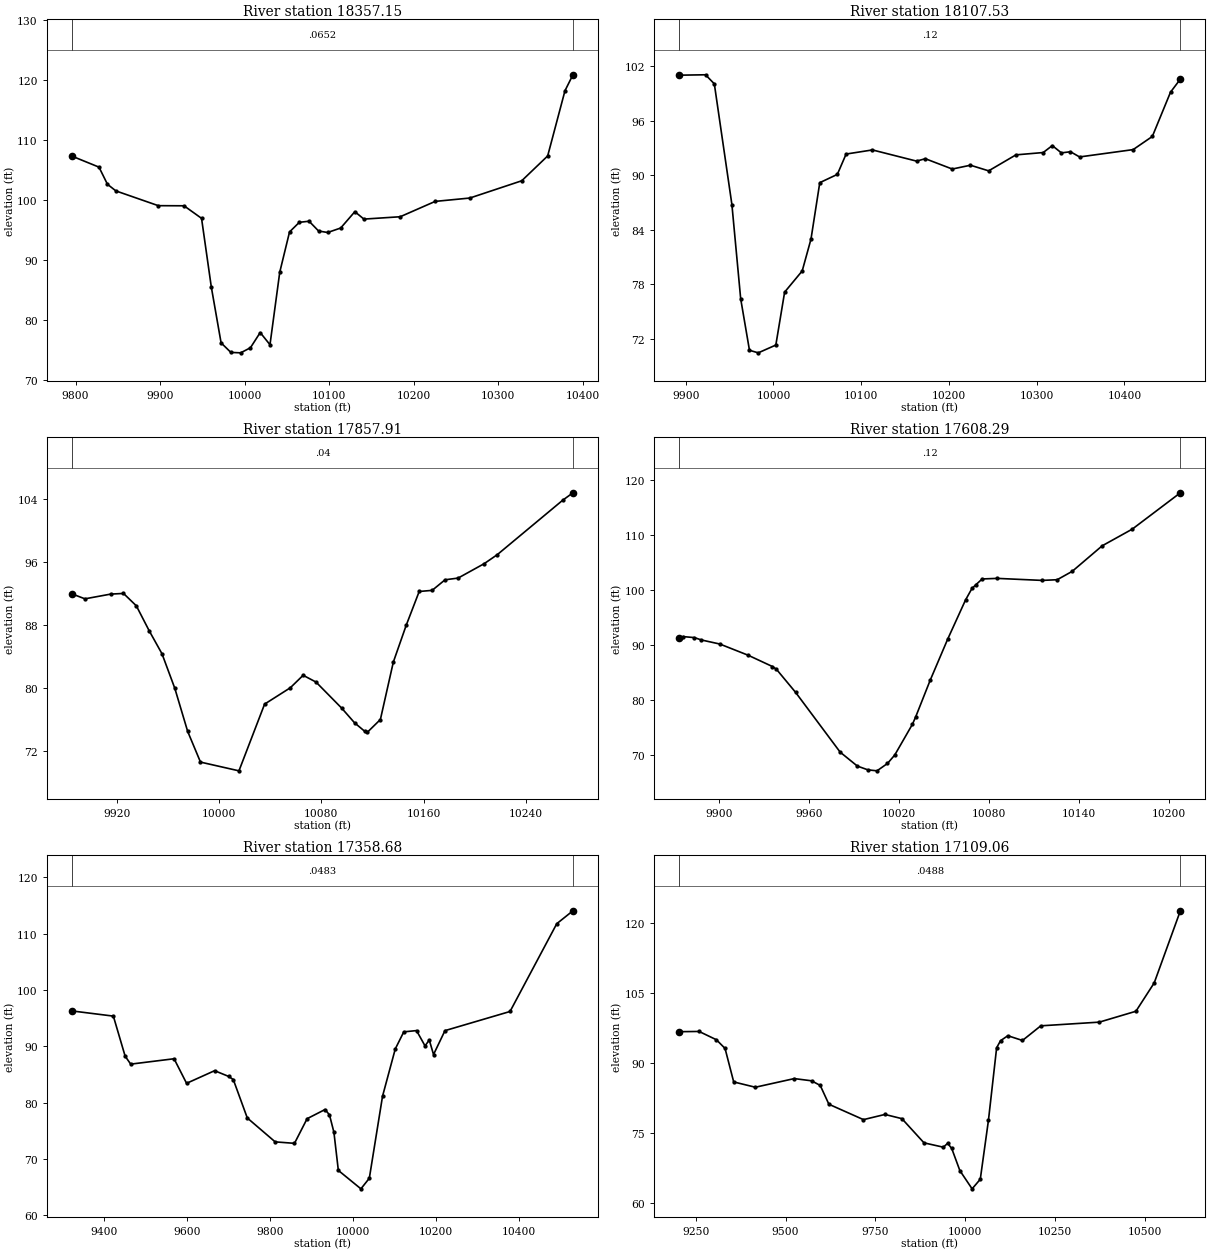
Type RM Length L Ch R = 1 ,18357.15,249.618000,249.618000,249.618000
XS GIS Cut Line= 6
839886.899826423747866.385021853839795.773748614747864.953075583
839738.295329895747874.632429583839619.232582026747943.862238502
839515.441250495747984.256744903  839325.8016589748025.716788042
#Sta/Elev= 30
9795.754107.35879827.657105.53119837.659102.6753 9847.66101.56659897.81699.10648
9928.23999.085379948.99196.996949960.55885.538519972.12676.232419983.69374.64241
9995.26174.5703810006.8375.41695 10018.477.9522610029.96  75.92510041.5388.02426
 10053.194.7273910064.6796.3296810076.23 96.513910087.4594.8839610098.1894.63312
10113.6195.3798910130.3798.10394 10141.196.8665110184.0297.2594610225.4499.81908
10266.39100.3782 10327.8103.254510358.51107.397910378.98118.2679 10388.4120.9279
#Mann= 3 , 0 , 0
9795.754  0.0652       09795.754  0.0652       0 10388.4  0.0652       0
#XS Ineff= 2 , 0
       0                               0
Bank Sta=9795.754,10388.4
Exp/Cntr=0.3,0.1

Type RM Length L Ch R = 1 ,18107.53,249.618100,249.618100,249.618100
XS GIS Cut Line= 6
839794.681584377 747647.58731128839688.671844415747653.595902704
839632.838324113747657.043611586839571.184438639747658.890999211
839501.822487605747666.109603044839234.169438962747739.178470743
#Sta/Elev= 30
 9892.82100.99669922.549101.04039932.565100.04349952.597 86.77969962.61476.41601
 9972.6370.757149982.64670.4752410002.6871.33164 10012.777.1495610032.7479.47717
10042.7682.9786110052.7789.1804610072.7990.0903710082.7992.32641 10112.892.77922
10163.0691.5509310173.1191.81329 10203.890.6792810224.5391.0990510245.2690.48043
10276.3692.2369110307.4692.4925510317.8293.2573910328.1992.4545310338.5592.58093
10348.9292.0093110409.9792.8144110431.8594.2603710452.5899.1271810463.81100.5657
#Mann= 3 , 0 , 0
 9892.82    0.12       0 9892.82    0.12       010463.81    0.12       0
#XS Ineff= 2 , 0
       0                               0
Bank Sta=9892.82,10463.81
Exp/Cntr=0.3,0.1

Type RM Length L Ch R = 1 ,17857.91,249.618000,249.618000,249.618000
XS GIS Cut Line= 6
839795.011569988747414.748872167839776.800783244747412.245214259
839630.792785162747400.605089275839567.212755535747393.703990198
839501.629155266747383.635411778839407.143946284747363.633575995
#Sta/Elev= 30
9885.068 91.94229895.17491.317999915.29191.916969925.32592.001689935.35990.43546
9945.39387.280239955.42784.361549965.46179.982129975.49574.535639985.52970.64186
10015.6269.5351110035.6877.9858910055.7580.0497910065.8181.6354410075.87 80.7794
10095.9977.4720210106.0475.6171710113.8874.5540410116.1274.4319810126.2376.03454
10136.3583.3087210146.4787.9874610156.5892.24941 10166.7 92.390810176.8293.73081
10186.9993.94569 10207.495.7707310217.6196.9062410268.72103.792210276.82104.7491
#Mann= 3 , 0 , 0
9885.068    0.04       09885.068    0.04       010276.82    0.04       0
#XS Ineff= 2 , 0
       0                10047.74       0
Bank Sta=9885.068,10276.82
Exp/Cntr=0.3,0.1

Type RM Length L Ch R = 1 ,17608.29,249.618000,249.618000,249.618000
XS GIS Cut Line= 6
839867.168345397747261.469709064 839823.28508987747230.342728734
839796.703877158 747207.65472548839768.516487304747180.933594372
839709.126651523747143.569890733839572.911240427747149.330286043
#Sta/Elev= 30
9873.38991.301799875.94391.575989883.394 91.39339887.94590.969449900.32690.22433
9919.31488.174869935.44286.127259938.10585.623619950.84681.436449980.56770.56319
9992.04668.02411    999967.3435410005.1567.1579610012.1468.4984810016.9770.02662
10028.78 75.629310030.9276.94854 10040.683.6213110052.4191.1832810064.2398.25384
10068.48100.327910071.17101.0291 10075.3102.0608 10085.3102.167210115.33101.7984
10125.34 101.92410135.35103.444210155.37108.095810175.39111.1221 10207.5117.7387
#Mann= 3 , 0 , 0
9873.389    0.12       09873.389    0.12       0 10207.5    0.12       0
#XS Ineff= 2 , 0
       0                               0
Bank Sta=9873.389,10207.5
Exp/Cntr=0.3,0.1

Type RM Length L Ch R = 1 ,17358.68,249.618000,249.618000,249.618000
XS GIS Cut Line= 6
840517.370302605747282.640062116840274.337038163747150.221133671
840101.640940582747061.123849496839986.986410562747009.252057508
839849.890426125746958.457442521839396.976463438746858.653763151
#Sta/Elev= 30
9323.09196.284979422.66395.366619451.05988.256259464.46586.837919568.96987.79494
9599.10383.429289666.62785.674049700.38484.659939711.63684.102239745.39477.27793
9812.583 73.03289859.113 72.77299889.52777.150419932.81378.779899943.46877.81749
9954.12274.734879964.77667.9656610019.1664.6921110039.4366.5737610071.2681.14194
10101.9889.5434510122.4692.5700810153.1892.7956610173.6590.0754210183.8991.12241
10194.1388.5429110221.7292.7889210378.45 96.187110491.09111.780210530.03114.0729
#Mann= 3 , 0 , 0
9323.091  0.0483       09323.091  0.0483       010530.03  0.0483       0
#XS Ineff= 2 , 0
       09819.549                       0
Bank Sta=9323.091,10530.03
Exp/Cntr=0.3,0.1

Type RM Length L Ch R = 1 ,17109.06,249.618100,249.618100,249.618100
XS GIS Cut Line= 6
840670.347632024747180.868281095840180.621161674746852.617332021
840114.506770871746811.899660535  840055.5551962746778.305200097
839919.733302947746704.889203577839423.551439055746802.939426385
#Sta/Elev= 30
9204.603 96.71429259.26196.764319307.474 94.98949331.58193.128729355.687 85.9537
9415.95384.817399524.43386.669339572.64686.194539596.75285.200089620.85981.17259
9717.14977.879579776.96678.990259824.25878.08902 9885.7572.906679939.66671.97631
9951.63572.807999962.97571.704219985.65466.9650210019.74 63.058310042.5265.11656
10065.2977.7509310088.0693.2691310098.8994.7826310119.2795.8490510160.05 94.8333
10211.0197.9689110374.11 98.760210476.04101.089910527.01107.166210599.84122.6084
#Mann= 3 , 0 , 0
9204.603  0.0488       09204.603  0.0488       010599.84  0.0488       0
#XS Ineff= 2 , 0
       09647.987                       0
Bank Sta=9204.603,10599.84
Exp/Cntr=0.3,0.1

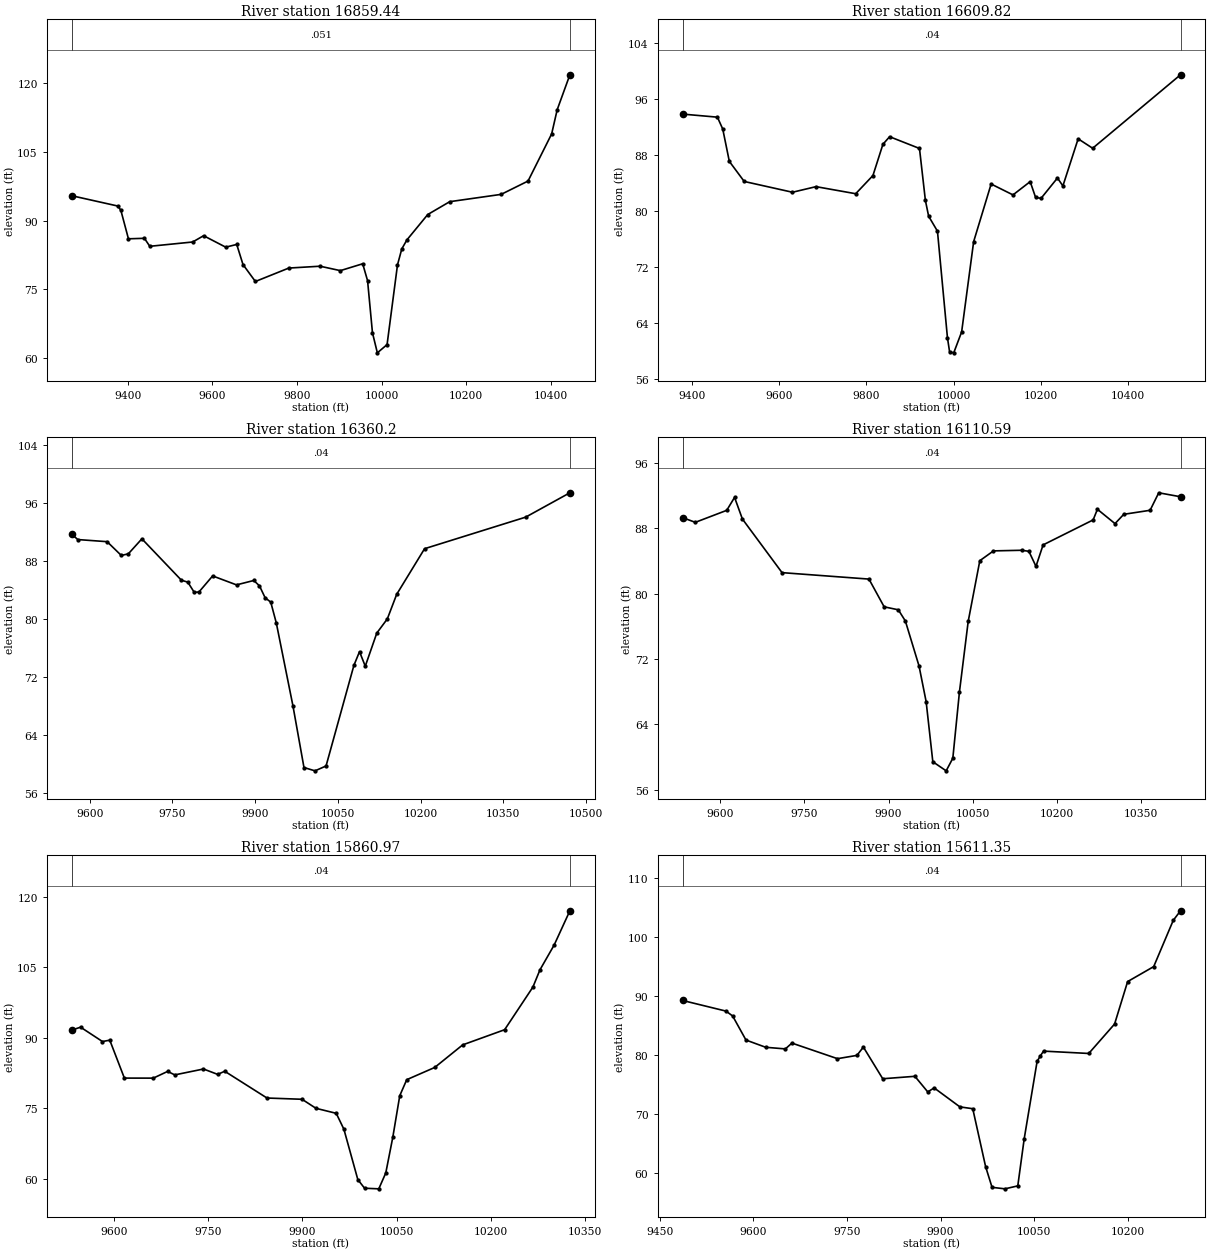
Type RM Length L Ch R = 1 ,16859.44,249.618000,249.618000,249.618000
XS GIS Cut Line= 6
840692.284989318747064.077762921840459.656850051746887.158494152
840299.553476252746745.667154515840214.256009301746648.023430477
840066.917346518746430.215954889839861.698973367746243.411536679
#Sta/Elev= 30
9267.71695.419419376.47993.168139383.49792.23308  9401.486.011769439.18986.11961
9451.85984.373689553.22485.313379579.11586.686939631.29884.184689657.389 84.7777
9672.167 80.38819701.46676.684049780.46579.618019854.34280.021029902.27179.05606
9955.08180.555419966.63876.862259978.19465.479899989.75161.0915310012.7462.89306
10037.3680.31578 10047.583.7990310059.6185.7707410108.9291.3207910160.8594.12489
10282.39 95.721310345.9198.6320110401.74108.9314 10414.8114.210310444.82121.8558
#Mann= 3 , 0 , 0
9267.716   0.051       09267.716   0.051       010444.82   0.051       0
#XS Ineff= 2 , 0
       09663.445                       0
Bank Sta=9267.716,10444.82
Exp/Cntr=0.3,0.1

Type RM Length L Ch R = 1 ,16609.82,249.618000,249.618000,249.618000
XS GIS Cut Line= 6
 840834.91383934746836.223969506840461.230885197746512.325423774
840320.404652841746379.737439806840262.916576961746332.153220752
840085.580062705746198.774245314839961.118680202746101.567989686
#Sta/Elev= 30
9378.29693.905619458.35193.465479470.60791.764899485.68587.144439519.854 84.2747
9630.556 82.73339684.57383.533569775.57482.522789815.12485.122899838.03189.58889
9853.37790.673979921.90588.992339935.45181.562819942.89879.308559963.14877.16569
9986.05861.934259990.96759.9208710000.4759.7782710018.5962.7621210046.1575.67478
10086.2683.9085910136.4282.3540310175.8284.2507210188.3381.9830310200.8481.86759
10238.3884.76809 10250.983.6391910285.8890.3712710319.1589.0222610520.7199.52477
#Mann= 3 , 0 , 0
9378.296    0.04       09378.296    0.04       010520.71    0.04       0
#XS Ineff= 2 , 0
       09915.183                       0
Bank Sta=9378.296,10520.71
Exp/Cntr=0.3,0.1

Type RM Length L Ch R = 1 , 16360.2,249.618100,249.618100,249.618100
XS GIS Cut Line= 6
840823.109146845746380.581133615840640.877847794746246.571163131
840516.023287711746202.286342361840306.696468646746171.817761701
840195.712756286746116.859294908840027.277593592745996.389062785
#Sta/Elev= 30
9567.46291.630589578.239 90.9147  9631.4  90.6239657.12488.726359669.86788.94958
9694.48391.016199766.11985.319799777.77685.050149789.43383.650479797.94483.69176
9822.81185.908199866.11384.676379897.46785.281429907.73784.546039918.00682.90847
9928.25582.298879938.32179.431089968.50268.021869988.51559.5321210008.5359.07548
10028.5659.74489 10079.173.5941110089.2875.4829610099.7273.47941 10120.678.03903
 10139.779.9880610156.7383.37677 10207.389.6564810390.65 93.9999 10470.997.35502
#Mann= 3 , 0 , 0
9567.462    0.04       09567.462    0.04       0 10470.9    0.04       0
#XS Ineff= 2 , 0
       0                10078.01       0
Bank Sta=9567.462,10470.9
Exp/Cntr=0.3,0.1

Type RM Length L Ch R = 1 ,16110.59,249.618000,249.618000,249.618000
XS GIS Cut Line= 6
840880.260323135746343.269083027840629.222366208746083.745911606
840592.554708957746035.607304307840516.538669726745921.118146198
 840425.09694678745803.341991772840310.378587797745665.138007414
#Sta/Elev= 30
9532.72389.277549555.53188.698599611.55490.164729625.52191.748939639.48889.10303
9710.16382.550419865.13481.762119892.21578.371439917.47878.008329930.04976.63732
9954.42671.138229967.069  66.7879978.98859.4377310002.7858.3263510014.65 59.8647
10026.5268.0113410042.0676.5890310062.7884.0102110087.1585.20902 10137.685.28471
10150.2685.1567510162.9283.3180910175.5885.9399710264.8288.9944110272.4590.29379
10303.8188.5411710319.4289.6786710366.3990.1710610381.7992.31098 10420.691.82374
#Mann= 3 , 0 , 0
9532.723    0.04       09532.723    0.04       0 10420.6    0.04       0
#XS Ineff= 2 , 0
       09923.862                       0
Bank Sta=9532.723,10420.6
Exp/Cntr=0.3,0.1

Type RM Length L Ch R = 1 ,15860.97,249.618000,249.618000,249.618000
XS GIS Cut Line= 6
841004.090245753746286.910925951840951.257587328746197.955150874
840895.592880799  746097.2958899840840.781955022745989.801162831
840684.171014578745669.095043677840638.976532164745582.816370471
#Sta/Elev= 30
9532.66291.620869546.51592.245959581.40789.192049593.03889.484619616.29981.42043
9662.35581.41219 9685.2182.839599696.63782.102019742.34683.352899764.95182.20954
9776.176 82.87359843.52677.183849899.37276.917469921.59774.995769953.85273.93138
9966.04870.556759988.273 59.8379    999958.0080210021.6557.8789410032.79 61.2559
10043.9368.8101910055.0677.67836 10066.281.0840910110.7683.6812210155.3188.47973
10222.1491.70335 10267.2100.766210278.49104.444510301.07109.707110326.11116.9868
#Mann= 3 , 0 , 0
9532.662    0.04       09532.662    0.04       010326.11    0.04       0
#XS Ineff= 2 , 0
       09885.607                       0
Bank Sta=9532.662,10326.11
Exp/Cntr=0.3,0.1

Type RM Length L Ch R = 1 ,15611.35,249.618000,249.618000,249.618000
XS GIS Cut Line= 6
841163.439711124 746280.19621391841123.529780014746174.112373785
841093.556957567 746079.48363476841068.266477343745987.846762593
840973.212543137745615.647726407840942.388899542745513.869063231
#Sta/Elev= 30
9486.49489.243959556.15287.440699566.83686.614649588.20482.537339619.88581.31029
9651.35481.037019661.84482.021439734.87279.381469765.99379.938999776.36781.34308
9807.40175.981429858.927 76.39519879.53873.756939889.84374.427939931.06471.21566
9951.67570.906499972.28561.09114 9982.59 57.591410003.2157.3349110023.8457.83544
10034.1665.83922 10054.878.9118210059.8879.8361410065.1480.6627510137.5980.26401
10178.9985.2495210199.8992.4414110241.6994.9771810273.03102.812510284.66104.4331
#Mann= 3 , 0 , 0
9486.494    0.04       09486.494    0.04       010284.66    0.04       0
#XS Ineff= 2 , 0
       09849.957                       0
Bank Sta=9486.494,10284.66
Exp/Cntr=0.3,0.1

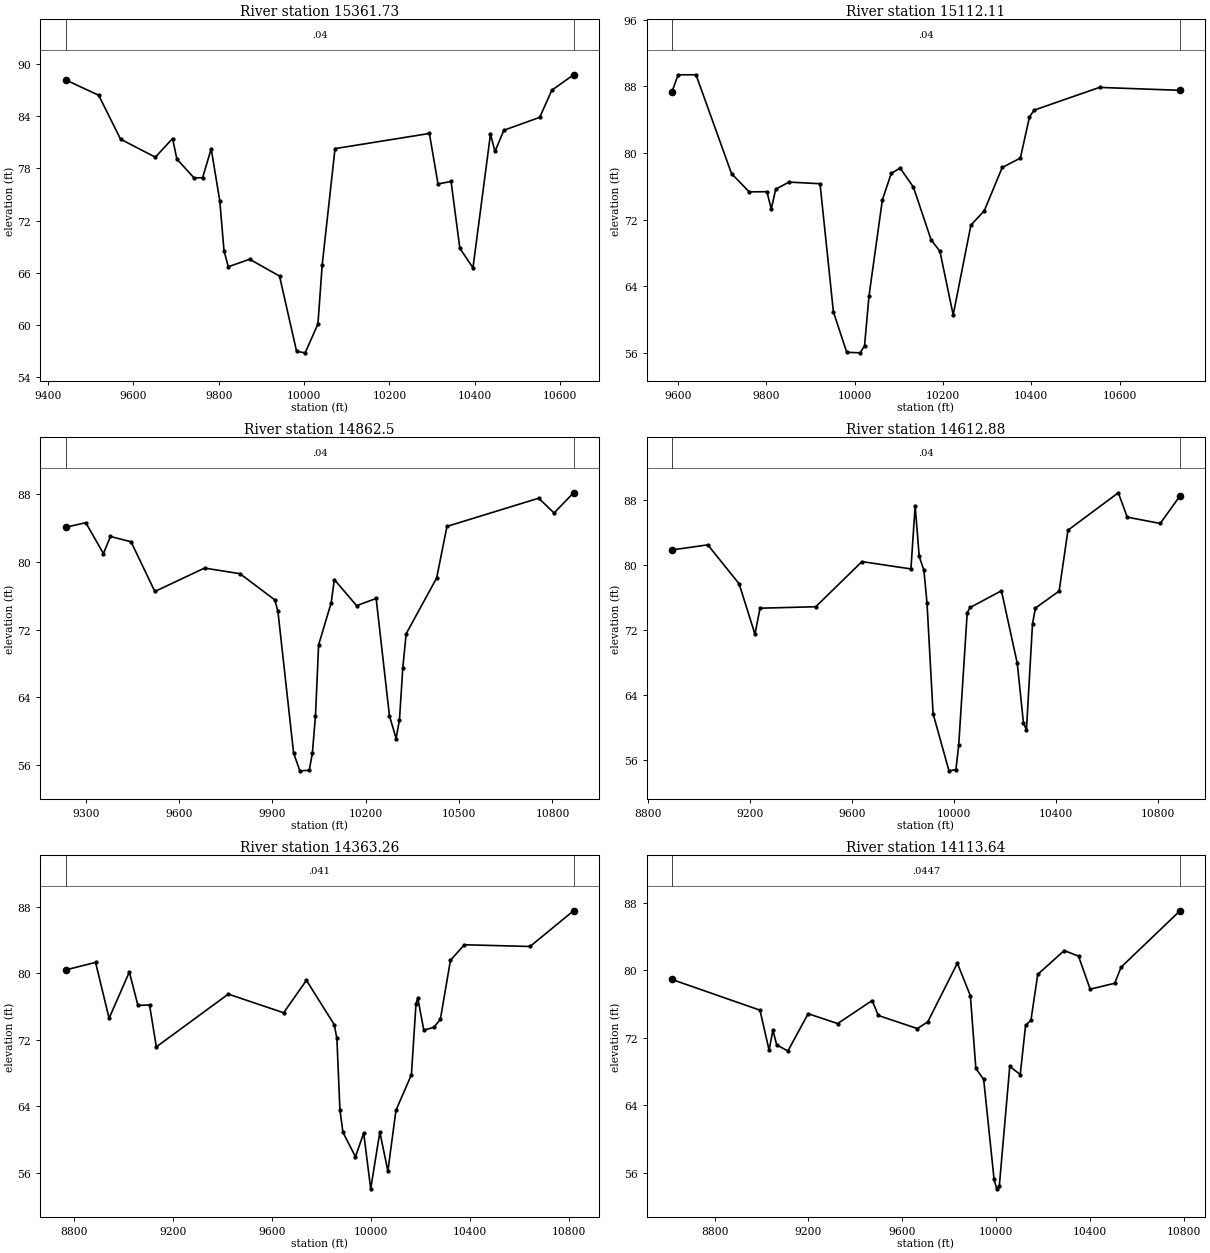
Type RM Length L Ch R = 1 ,15361.73,249.618100,249.618100,249.618100
XS GIS Cut Line= 6
841334.650017113746309.574177414841294.985865727746155.924346737
841276.244978657746030.823993672841252.024862733745511.284658901
841215.057415711745325.422767953841151.361029746745141.220641029
#Sta/Elev= 30
9441.05388.177199518.78186.40478 9570.0481.360129651.501 79.29079691.92881.43405
9702.00679.069239742.25576.910899762.32876.934459782.40180.254969802.454 74.2939
9812.46668.539589822.47866.700239872.52367.565229942.52865.632689982.53156.98339
10002.5356.8130910032.5360.1255310042.5366.9372710072.5580.2740610293.6382.01399
10313.8876.2183310344.4776.4982510364.9968.8281110395.7766.5813810436.82  81.949
10447.28 79.945310468.1882.3847910552.1883.86744 10580.586.9803710631.4488.75695
#Mann= 3 , 0 , 0
9441.053    0.04       09441.053    0.04       010631.44    0.04       0
#XS Ineff= 2 , 0
       09777.036        10127.92       0
Bank Sta=9441.053,10631.44
Exp/Cntr=0.3,0.1

Type RM Length L Ch R = 1 ,15112.11,249.618000,249.618000,249.618000
XS GIS Cut Line= 6
841514.783595968746188.697581159841496.541909778 746001.50556141
841527.963382185 745649.88433179841523.175701832745504.706640039
841473.667126462745300.644849208841371.991532322 745069.58330047
#Sta/Elev= 30
9586.57687.329759600.45989.383569640.97889.387099721.32677.538719761.36575.33973
9801.38175.364489811.38273.294489821.38375.659889851.428 76.51399921.71876.31983
9951.938 60.96029982.15756.0981210012.3956.0311410022.4856.8733810032.5662.84964
10062.81 74.3801 10082.9 77.554210102.9778.2029810133.06 75.918710173.07 69.5935
10193.0768.2151310223.1260.5832610263.2671.3556910293.5473.0742110334.0878.26439
10375.1379.3880810395.8584.3232810406.2185.1422110554.3287.8725910736.5787.52306
#Mann= 3 , 0 , 0
9586.576    0.04       09586.576    0.04       010736.57    0.04       0
#XS Ineff= 2 , 0
       09860.788        10095.09       0
Bank Sta=9586.576,10736.57
Exp/Cntr=0.3,0.1

Type RM Length L Ch R = 1 , 14862.5,249.618000,249.618000,249.618000
XS GIS Cut Line= 6
842003.809797897746511.713579017841887.730061706746284.228938081
841812.871724384746077.554828512841711.321080873745550.278644116
841599.784618746745295.047614479841433.253169349744998.487455854
#Sta/Elev= 30
9235.018 84.05219300.20784.594399356.87580.953629379.364 82.96659445.60782.34723
9522.10676.485389681.78279.243849795.69178.582459907.57975.49147 9917.6674.13883
9968.03657.442199988.13455.3379310018.2855.4033110028.3357.4044410038.3861.84406
10048.4270.1927710088.7975.1466310098.9177.89044 10170.674.8100410233.3375.66452
   1027661.8431810297.5159.1462510308.26 61.358110319.0267.5157410329.7871.50067
10427.7478.07309 10460.984.15754 10755.787.4830910805.0985.7335410867.6888.12096
#Mann= 3 , 0 , 0
9235.018    0.04       09235.018    0.04       010867.68    0.04       0
#XS Ineff= 2 , 0
       09877.994        10341.57       0
Bank Sta=9235.018,10867.68
Exp/Cntr=0.3,0.1

Type RM Length L Ch R = 1 ,14612.88,249.618100,249.618100,249.618100
XS GIS Cut Line= 6
842756.490410618746447.933076644842143.790601386745807.118166017
842043.476345746745729.151225738841903.148655762745658.738505194
841836.996641529745600.181204804841449.550410691744979.574074387
#Sta/Elev= 30
8895.04981.844579035.55982.468629158.41577.659879220.43771.453679240.31974.65987
9458.74574.841719639.87980.403339831.921 79.50159848.54487.275399864.37381.04749
9882.814 79.33639894.98475.307249918.86561.654599981.17654.6113110008.3154.75804
 10019.257.7403310052.7174.1286210064.13 74.746710186.7976.8090410248.9567.86074
10272.9260.5545610284.91 59.647310308.6272.7402810320.2174.6761610412.97  76.772
10447.7684.2785410645.0388.88855 10680.185.8846410809.4485.1054310886.9988.50652
#Mann= 3 , 0 , 0
8895.049    0.04       08895.049    0.04       010886.99    0.04       0
#XS Ineff= 2 , 0
       09774.341         10381.1       0
Bank Sta=8895.049,10886.99
Exp/Cntr=0.3,0.1

Type RM Length L Ch R = 1 ,14363.26,249.618000,249.618000,249.618000
XS GIS Cut Line= 6
  843042.9451527746265.651934585842513.892425194745789.583274648
842133.752295015745507.564043852841859.770446539 745288.40293685
841699.437142955745121.759502014841519.940547475744897.884564264
#Sta/Elev= 30
8764.64780.404068886.18781.308668940.92774.585549022.82980.155949057.56576.13135
9104.42576.195749132.01771.148199422.89977.49534 9646.8375.25152 9738.9979.15514
9851.62773.815479862.18872.159939874.50863.525789886.82760.853129937.23257.92916
9970.54260.778599998.89454.0664210035.8460.88749 10068.4 56.212110100.9763.50627
10163.6167.8063810182.0576.33185 10189.3 77.021610213.6873.15259   1025473.49862
10280.6374.4590810321.4581.5703710377.7283.43362 10643.283.2252210819.2487.52184
#Mann= 3 , 0 , 0
8764.647   0.041       08764.647   0.041       010819.24   0.041       0
#XS Ineff= 2 , 0
       09815.072        10184.94       0
Bank Sta=8764.647,10819.24
Exp/Cntr=0.3,0.1

Type RM Length L Ch R = 1 ,14113.64,249.618000,249.618000,249.618000
XS GIS Cut Line= 6
843348.627292297746065.524896592842716.016989457745551.013218438
 842408.89620095745358.556450722841965.974272581745119.428767165
841821.441834913745007.171981393841608.006395195744795.682208916
#Sta/Elev= 30
8618.53378.88688 8993.7175.247319032.53170.516249049.00472.890299064.94171.13651
9112.75270.408049199.05174.828689325.04173.662259471.97576.393969498.31974.61802
9664.77773.067659709.18873.865549835.30280.818059890.75776.957199914.17668.33685
9947.48467.040389991.89555.18045   1000354.0692910014.1454.39734 10058.768.58151
 10103.467.6200610126.1573.45078 10148.974.0368810178.0179.4896510290.7382.31302
10351.7881.6598110401.5377.7403310506.2378.4369810533.3180.3459810784.5987.03139
#Mann= 3 , 0 , 0
8618.533  0.0447       08618.533  0.0447       010784.59  0.0447       0
#XS Ineff= 2 , 0
       09835.946        10166.43       0
Bank Sta=8618.533,10784.59
Exp/Cntr=0.3,0.1

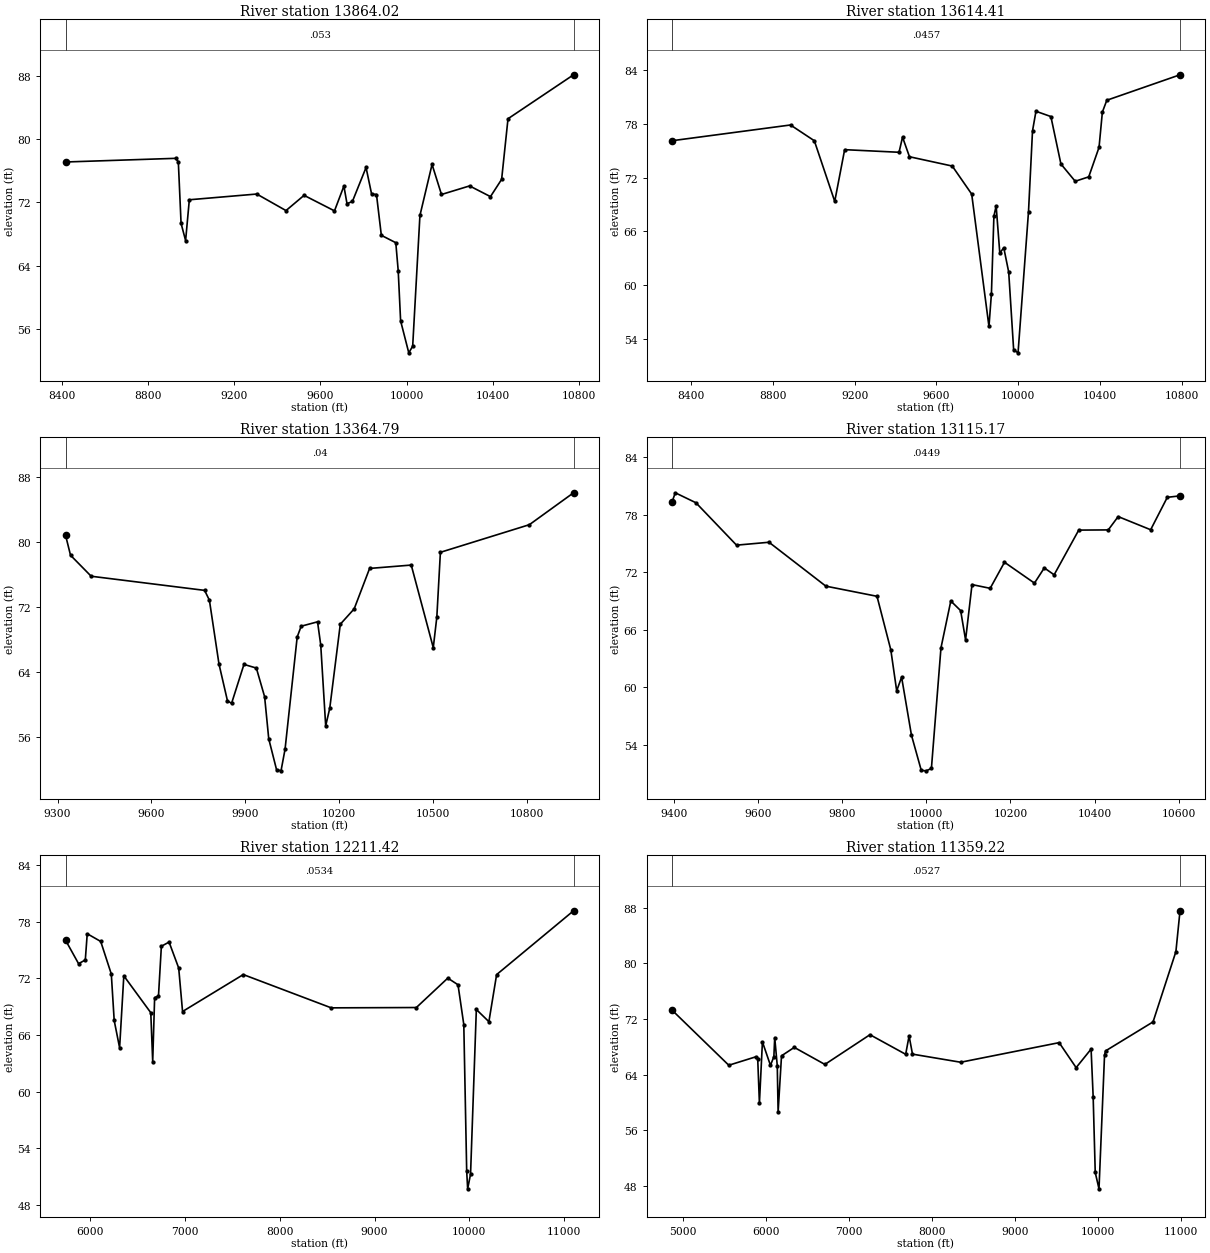
Type RM Length L Ch R = 1 ,13864.02,249.618000,249.618000,249.618000
XS GIS Cut Line= 6
843613.850092399745954.513839024843235.952420995745632.624709956
 842871.31723427745355.683356013842550.339675322745153.221369567
842041.808586777744876.463233798841700.349740561744595.568826883
#Sta/Elev= 30
8417.48477.110218927.90377.571048940.668 77.13558953.43369.361038974.45567.18342
8991.72972.339079304.44873.063189440.03670.972939523.85972.898629664.91670.93578
9708.56274.06741 9722.9271.848329748.01972.123689811.322 76.41479836.98573.06891
 9859.67 73.00389882.19767.84882 9949.2366.916089960.40363.392559971.575  57.049
10009.4753.0087210027.5453.8439610061.1770.35354 10117.4 76.802210161.1273.00538
10291.4474.08792 10388.372.7360410440.07 74.916310469.6282.5709210773.5988.12292
#Mann= 3 , 0 , 0
8417.484   0.053       08417.484   0.053       010773.59   0.053       0
#XS Ineff= 2 , 0
       09804.109        10320.92       0
Bank Sta=8417.484,10773.59
Exp/Cntr=0.3,0.1

Type RM Length L Ch R = 1 ,13614.41,249.618100,249.618100,249.618100
XS GIS Cut Line= 6
843796.463430542745856.014312956843140.776924742745308.757350024
842855.443462759745096.359689243842232.505997056 744668.21268437
842065.620159546744540.987228011841832.275712981 744340.14482603
#Sta/Elev= 30
8307.16576.11755 8886.6977.875229003.11776.114919102.85569.347599151.28375.12079
9417.26974.829629434.29176.521359468.20674.330649677.43173.290819772.35770.16316
9856.81255.388179868.87759.049219880.94267.694769891.91368.848579909.78663.58086
9929.20264.174429953.33261.456079977.46352.79128    999952.4481810050.1668.21507
10069.7177.2112110086.5979.40488 10159.578.8159310208.5873.52189 10278.471.59407
10344.5872.0858510394.9475.3814310411.2279.3134410432.9680.6349510790.7983.47713
#Mann= 3 , 0 , 0
8307.165  0.0457       08307.165  0.0457       010790.79  0.0457       0
#XS Ineff= 2 , 0
       09751.669        10393.61       0
Bank Sta=8307.165,10790.79
Exp/Cntr=0.3,0.1

Type RM Length L Ch R = 1 ,13364.79,249.618000,249.618000,249.618000
XS GIS Cut Line= 6
843117.159389191745065.211045965842606.751701714744625.472152275
842559.236315903744586.687469865842416.044476823744467.473678445
842261.841453082744338.720226145841820.905943529744099.490007991
#Sta/Elev= 30
9325.28980.859329341.33978.379969407.33675.794489769.91374.054219785.23472.84743
9815.87564.981849842.919 60.46359856.11860.144789895.716 64.93979935.31564.48839
9961.71460.961639974.91355.778969999.74751.9944810014.1751.8347710027.0854.50259
10065.8568.31585 10078.669.6426510130.9170.1819610141.1267.3279510156.93 57.3791
10169.9459.5421210203.6469.8860710248.0271.7788510297.3276.75609 10430.477.16991
10500.8467.0059510512.21 70.774910523.5978.7407410808.02 82.1418 10949.286.07084
#Mann= 3 , 0 , 0
9325.289    0.04       09325.289    0.04       0 10949.2    0.04       0
#XS Ineff= 2 , 0
       09733.606        10287.28       0
Bank Sta=9325.289,10949.2
Exp/Cntr=0.3,0.1

Type RM Length L Ch R = 1 ,13115.17,903.746000,903.746000,903.746000
XS GIS Cut Line= 2
843291.699723442744754.518607531842259.169240153 744128.83681344
#Sta/Elev= 30
9395.59179.305229403.42480.291169452.54979.249149549.02974.826829626.21375.12981
9761.28470.548859882.82669.490929915.65163.899929929.59759.63235 9941.2961.05426
9964.67555.008359988.06151.322029999.75451.2806110012.1351.5344710034.8364.10735
10058.2268.99984 10081.667.99511 10093.3 64.939810108.6170.7122810151.7670.32267
10185.7973.0416410256.9970.8658710280.3872.4518310303.7671.7341210362.2376.39702
10432.3876.4180510455.9477.8080510533.1276.43437 10572.779.81673 10602.979.97202
#Mann= 3 , 0 , 0
9395.591  0.0449       09395.591  0.0449       0 10602.9  0.0449       0
#XS Ineff= 2 , 0
       0                               0
Bank Sta=9395.591,10602.9
Exp/Cntr=0.3,0.1

Type RM Length L Ch R = 1 ,12211.42,852.203500,852.203500,852.203500
XS GIS Cut Line= 6
844978.087589746747500.651395408844469.444627771744828.425231796
844247.222405549 744460.36967624843754.166849993743967.314120685
843559.722405549743842.314120685842285.631653495743682.935471186
#Sta/Elev= 30
5736.881 76.05465874.79773.557385945.96573.950855966.29976.731636108.63675.91564
6220.47272.460076250.97367.534266308.13164.639916352.64272.268416637.31568.35975
6657.64963.178526677.98369.951746718.65170.134046749.15275.403096830.48775.85015
6932.15673.095256972.82468.484527614.22572.40244 8542.9468.872619441.79568.90654
9773.61372.02556 9881.5271.321119942.67567.103519973.25351.553049983.44549.67944
10014.0251.2415510075.1868.6996110207.6867.4067910289.2272.3977111101.6179.16703
#Mann= 3 , 0 , 0
5736.881  0.0534       05736.881  0.0534       011101.61  0.0534       0
#XS Ineff= 2 , 0
       09491.003                       0
Bank Sta=5736.881,11101.61
Exp/Cntr=0.3,0.1

Type RM Length L Ch R = 1 ,11359.22,1464.799100,1464.799100,1464.799100
XS GIS Cut Line= 6
845665.587589746747813.151395408845025.000183326744981.203009573
844295.461584413743753.667180696843654.079772271742925.583031965
843446.778042719742692.774410844843139.183054404742386.840878421
#Sta/Elev= 30
4865.26373.300595550.29565.363035878.37966.584455898.884 66.3206 5919.3959.90373
5955.73868.727426052.67465.343716093.68566.592196103.93769.342026134.69565.29755
6144.94858.651616185.95866.720336339.74867.930656708.84365.480817252.23369.75571
7682.84466.937867723.85569.581847764.86566.960898345.97865.794229533.08868.61486
 9737.7665.017749918.12467.689079943.10360.824059968.08249.9382610013.4347.58327
 10080.366.8357110092.7767.4278610664.9671.5969910940.5281.7072610990.1487.58347
#Mann= 3 , 0 , 0
4865.263  0.0527       04865.263  0.0527       010990.14  0.0527       0
#XS Ineff= 2 , 0
       08913.978                       0
Bank Sta=4865.263,10990.14
Exp/Cntr=0.3,0.1