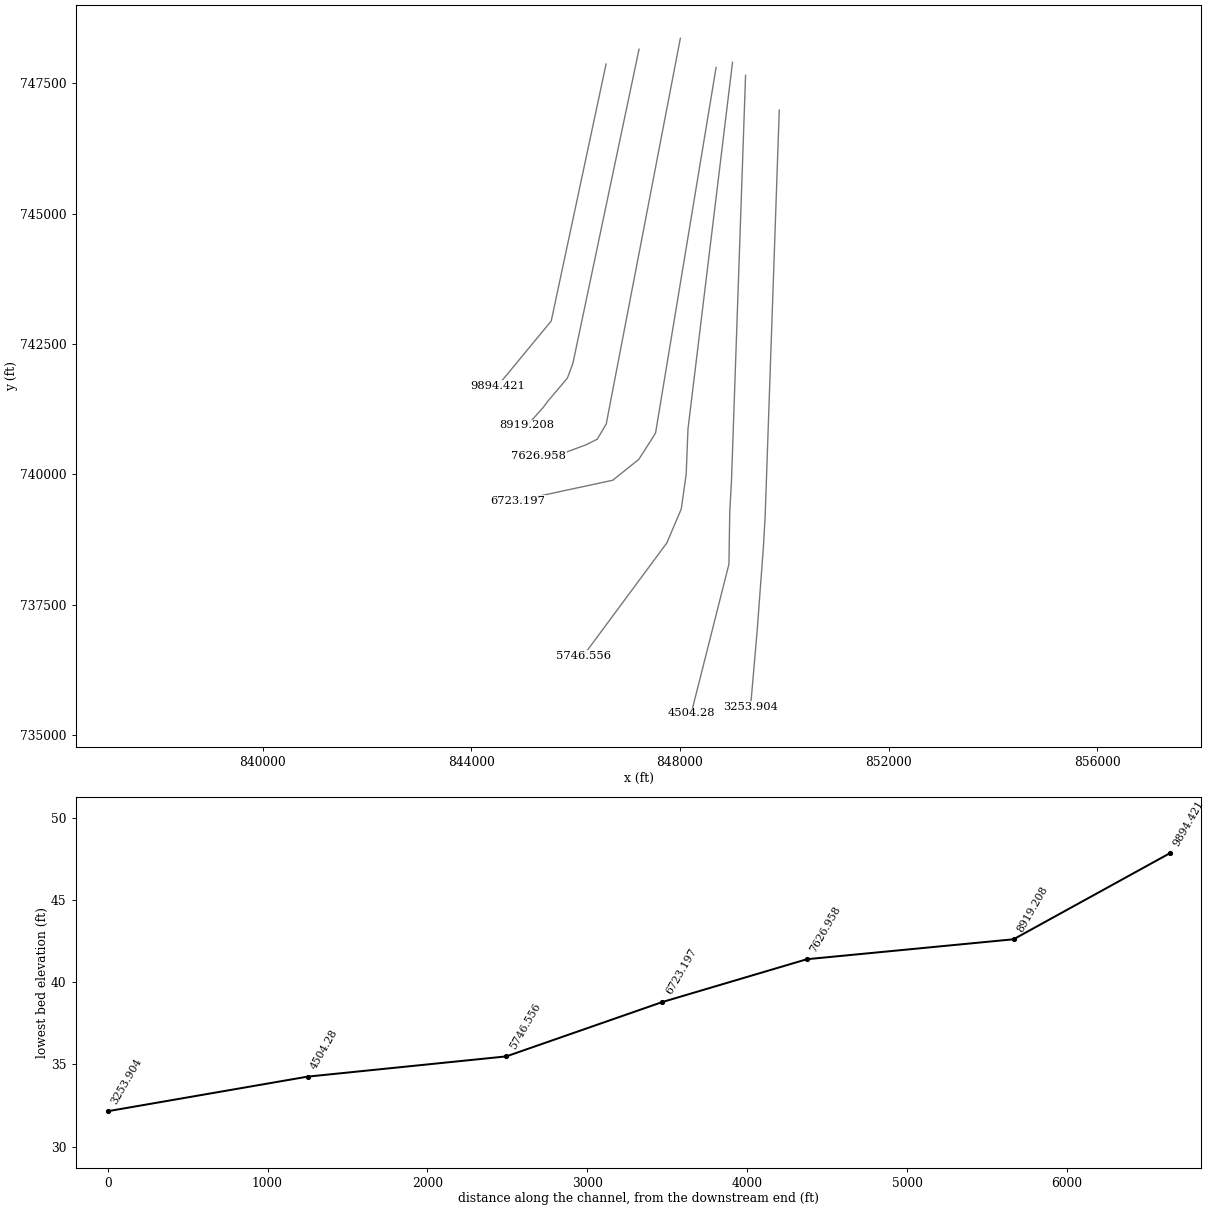
HEC-RAS study 8524_ras.prj: 8524

--- 8524_ras.g01 (geometry) --- (continued)

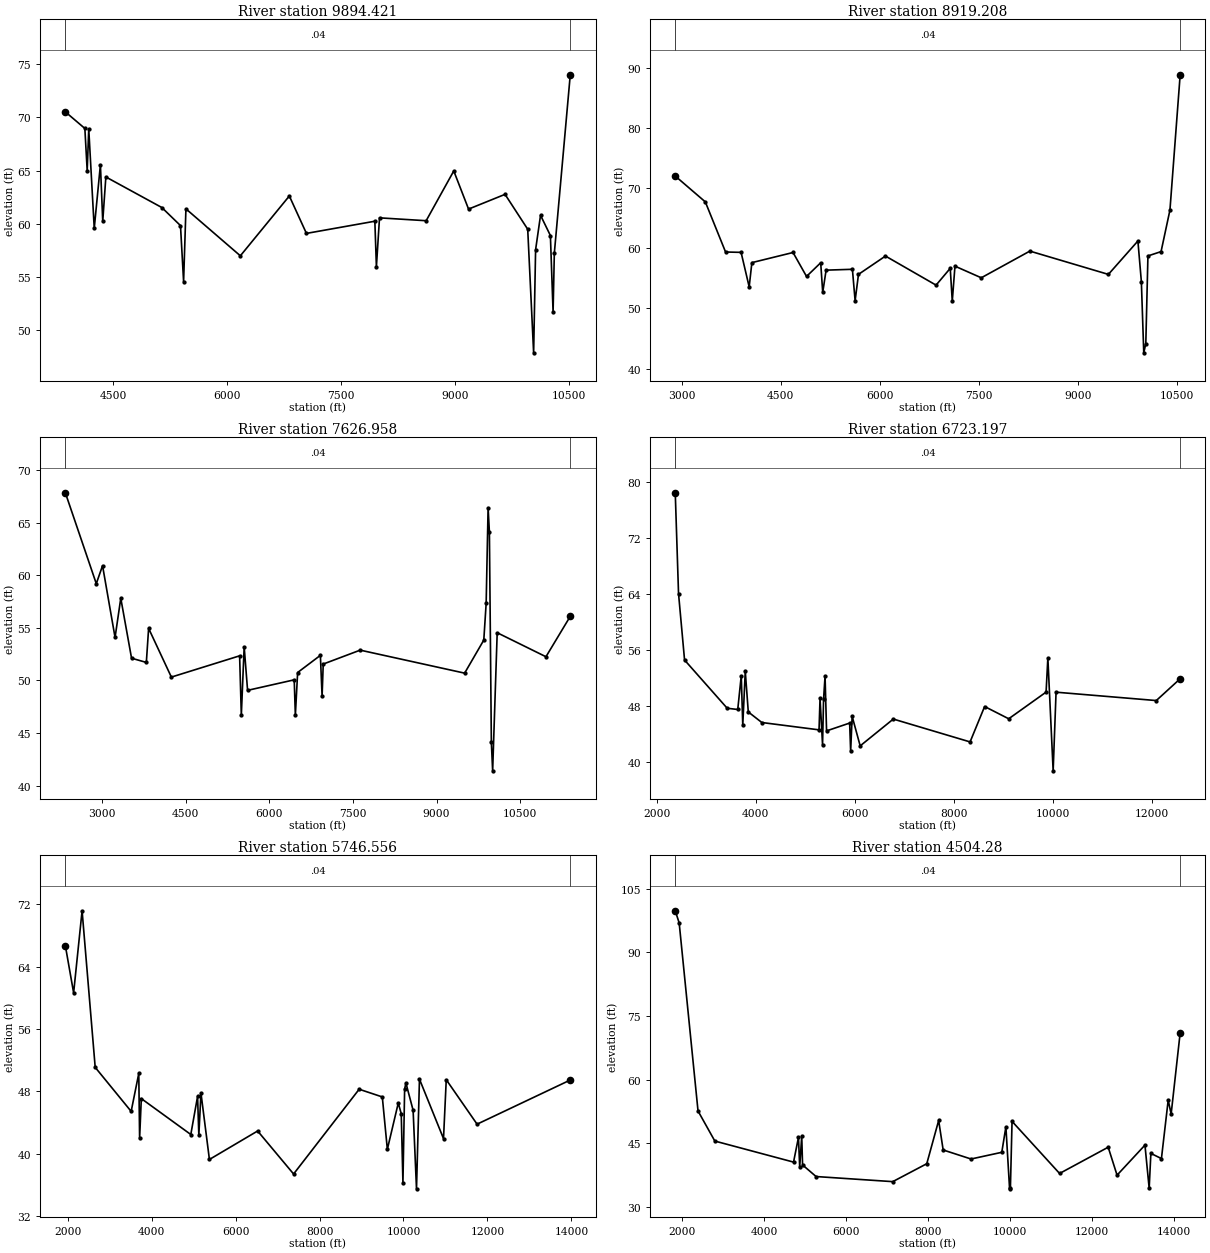
Type RM Length L Ch R = 1 ,9894.421,975.213200,975.213200,975.213200
XS GIS Cut Line= 3
846584.315888357747865.958108371845533.210542123742941.489467907
844511.111294437741703.425231796
#Sta/Elev= 30
3873.792 70.51834130.40368.958094161.07964.984674181.52968.92073 4253.7659.55733
4334.908 65.54154365.58460.228514406.48564.394775142.70361.51939 5388.1159.81838
5429.01154.553555459.68661.392796175.45456.976076819.64662.604487044.601 59.0842
7944.42460.230537964.87555.947738005.77660.547368619.29160.27787 8982.4464.95936
9176.95261.371039656.74962.758749955.00159.4757610032.8147.8477210058.7457.54973
10123.5860.7876610253.2558.8837610288.6351.6888710305.1257.2279310514.6474.00743
#Mann= 3 , 0 , 0
3873.792    0.04       03873.792    0.04       010514.64    0.04       0
#XS Ineff= 2 , 0
       0 7804.15                       0
Bank Sta=3873.792,10514.64
Exp/Cntr=0.3,0.1

Type RM Length L Ch R = 1 ,8919.208,1292.249800,1292.249800,1292.249800
XS GIS Cut Line= 6
847216.260332802748150.680330593845948.427368524742129.355607412
845842.674545818741846.527783661845462.003956103741397.264355768
845378.045816205741282.669689863845069.657935738740939.828244699
#Sta/Elev= 30
2900.84672.022423356.29967.726323662.87759.39018 3897.9259.331684020.55153.59142
4061.42857.624124684.80359.308824889.189 55.32725103.79357.602245134.45152.67012
5185.54856.373245584.09956.516345624.97651.289145676.07255.671616084.84358.71733
6851.28853.880227065.89356.681177096.55151.215287137.42857.036997535.97955.10226
8271.76659.540919461.09255.666649908.22861.222949960.47954.485069997.02642.62149
10027.86 44.159410060.2258.7366210259.0159.4583610393.5166.3655810548.42 88.8647
#Mann= 3 , 0 , 0
2900.846    0.04       02900.846    0.04       010548.42    0.04       0
#XS Ineff= 2 , 0
       07070.856        10303.17       0
Bank Sta=2900.846,10548.42
Exp/Cntr=0.3,0.1

Type RM Length L Ch R = 1 ,7626.958,903.761400,903.761400,903.761400
XS GIS Cut Line= 6
848007.926999468748359.013663927846587.500183326740967.314120685
846413.889072215740675.647454018846202.447117041740569.776576678
845707.674526897740386.141187666845291.710835283740350.440367718
#Sta/Elev= 30
2345.85467.845482900.425 59.2036 3012.56 60.91683236.82954.090843339.32557.81888
3532.45752.116853797.50351.716063838.27954.953934246.04250.32103 5469.3352.34272
5499.91246.696045550.88253.198245612.04749.06012 6447.9650.061176468.34846.68062
6509.12450.754966916.88752.387776947.46948.500426967.85751.559767630.47152.88392
9502.38450.696979845.83653.839259888.13457.330369923.04666.432099946.32164.08901
9981.23444.1249210004.51 41.407810085.9754.5391310959.9752.2557911395.6856.09888
#Mann= 3 , 0 , 0
2345.854    0.04       02345.854    0.04       011395.68    0.04       0
#XS Ineff= 2 , 0
       06544.122        10429.39       0
Bank Sta=2345.854,11395.68
Exp/Cntr=0.3,0.1

Type RM Length L Ch R = 1 ,6723.197,976.640900,976.640900,976.640900
XS GIS Cut Line= 6
848692.822832802747800.419913927847533.437643868740799.476481821
847465.999453933 740685.93475615847210.229085182740288.226128716
846712.586546186739889.653578723 844893.42712596739498.573031561
#Sta/Elev= 30
2371.48678.511072437.79864.107862559.43454.627113421.023   47.743633.88747.56296
3704.84152.39554 3735.2545.319293785.93253.00515 3846.7547.212894120.43145.70405
5275.97444.655575296.24749.161625346.92942.505675367.20148.991135397.61152.33776
 5428.0244.506715894.29145.625235914.56441.606465944.97346.578436107.15542.36599
6776.15346.196498327.01442.932278620.96847.988719107.51246.238299862.53850.04594
9898.209 54.924810005.1738.8027510063.8850.0349812088.6548.83895   1257151.95325
#Mann= 3 , 0 , 0
2371.486    0.04       02371.486    0.04       0   12571    0.04       0
#XS Ineff= 2 , 0
       05991.096        10300.85       0
Bank Sta=2371.486,12571
Exp/Cntr=0.3,0.1

Type RM Length L Ch R = 1 ,5746.556,1242.275400,1242.275400,1242.275400
XS GIS Cut Line= 6
849007.926999468747900.680330593848153.906433326740868.355787351
848120.172507518740011.094249973848026.121212458739340.696935461
847748.920923079738688.151395408846144.754256413736521.484728741
#Sta/Elev= 30
 1947.7866.671092144.89860.628132346.36771.149572658.64551.07049 3514.8945.42391
3696.21250.284653716.35941.973683756.65347.064724935.24942.460155096.42547.34294
5126.64542.346345177.01347.779045378.48239.258696526.85842.910897383.10337.39479
8944.49148.264639495.48647.276959615.57940.56012 9875.7846.49483 9946.3445.13282
9986.73236.2831310027.1248.2767710057.4249.0717110229.0845.5682210309.8735.49209
10380.5549.5596610953.1241.9309911018.3149.4861711752.3843.7837113971.53 49.4465
#Mann= 3 , 0 , 0
 1947.78    0.04       0 1947.78    0.04       013971.53    0.04       0
#XS Ineff= 2 , 0
       05807.301        10097.63       0
Bank Sta=1947.78,13971.53
Exp/Cntr=0.3,0.1

Type RM Length L Ch R = 1 , 4504.28,1250.376700,1250.376700,1250.376700
XS GIS Cut Line= 5
849257.926999468747650.680330593848987.093666135739859.013663927
848954.928477546739293.249659833848939.173035199738281.729046975
848216.260332802735421.513663927
#Sta/Elev= 30
 1825.1199.786441920.84996.922722381.12652.600752791.37445.519794712.53440.56034
4832.60646.386874862.62439.444614912.65446.650994932.66639.890555262.86637.15844
7133.99535.955867964.49640.178668254.671  50.3658364.73843.418889045.14941.29153
9795.77742.868519895.93948.881049986.08434.2600310006.1234.4934710046.1850.16109
11206.7437.8823712392.9144.0699312609.5137.4851913290.2744.5644113393.4134.39428
13434.6742.6107313692.5341.3892613857.56 55.150913929.7651.9051714149.9671.04416
#Mann= 3 , 0 , 0
 1825.11    0.04       0 1825.11    0.04       014149.96    0.04       0
#XS Ineff= 2 , 0
       05620.465        10563.62       0
Bank Sta=1825.11,14149.96
Exp/Cntr=0.3,0.1

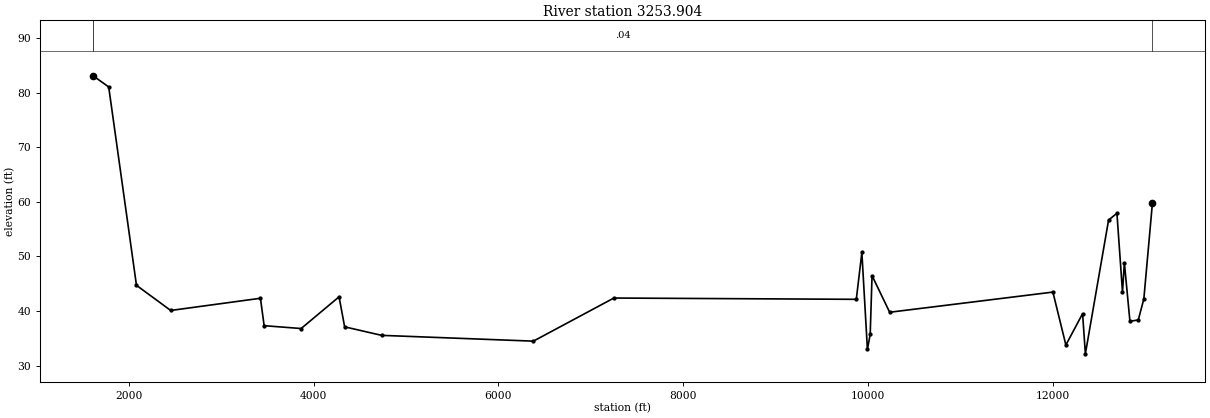
Type RM Length L Ch R = 1 ,3253.904,0.000000,0.000000,0.000000
XS GIS Cut Line= 5
849903.760332802746984.013663927849632.926999468 739192.34699726
849600.761810879738626.582993166849478.087589746736979.818062075
849353.087589746735542.318062075
#Sta/Elev= 30
 1615.6983.115181784.80581.069222084.98744.71319 2455.2140.103423425.79642.33937
 3465.8237.314263866.06236.792454276.309  42.6074336.34537.104884736.58735.54143
6377.57734.480317248.10342.382069870.14742.144329930.244 50.73499990.35532.97167
10020.4435.7259910040.4946.4777910231.0239.7768311996.2643.4714412136.7933.76866
12317.4739.5162712347.5832.1541112598.5356.6661212688.87 57.922312749.0943.45172
12769.17 48.857212829.3938.1243912919.7338.3581812979.9642.2264213072.9959.85455
#Mann= 3 , 0 , 0
 1615.69    0.04       0 1615.69    0.04       013072.99    0.04       0
#XS Ineff= 2 , 0
       04983.834         10449.7       0
Bank Sta=1615.69,13072.99
Exp/Cntr=0.3,0.1